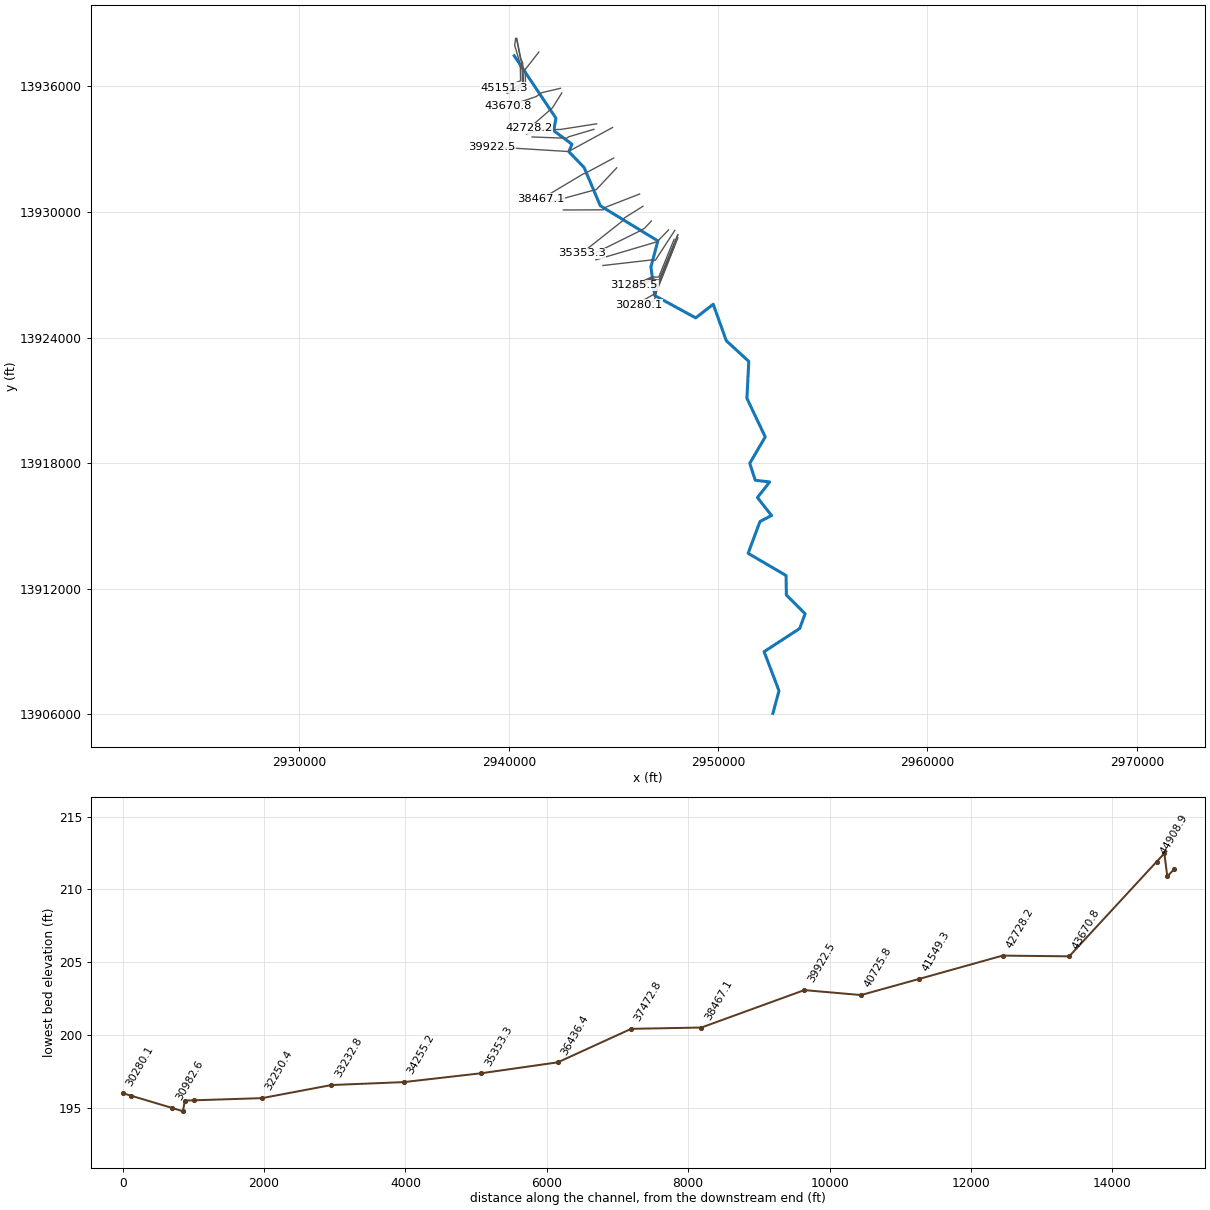
--- K166-00-00.prj (project) ---

Proj Title=K166-00-00
Current Plan=p08
Default Exp/Contr=0.3,0.1
English Units
Geom File=g01
Flow File=f08
Flow File=f09
Plan File=p03
Plan File=p08
Y Axis Title=Elevation
X Axis Title(PF)=Main Channel Distance
X Axis Title(XS)=Station
BEGIN DESCRIPTION:
Cypress Creek Watershed
Mound Creek
HCFCD Unit K166-00-00
Flood Hazard Model
10, 2, 1, 0.2%
Filename k166-00-00
Prepared by:  Halff Associates Inc  DATE:  March 24, 2004
Reviewed by:  _____________________  DATE:  __________________
STATUS (Final)
TROPICAL STORM ALLISON RECOVERY PROJECT
END DESCRIPTION:
DSS Export Rating Curves= 0
DSS Export Rating Curve Sorted= 0
DSS Export Volume Flow Curves= 0
DXF OffsetX= 0
DXF OffsetY= 0
DXF ScaleX= 1
DXF ScaleY= 10

--- K166-00-00.p08 (plan) ---

Plan Title=Effective FW 2013
Program Version=3.13
Short Identifier=Eff FW 2013
Geom File=g01
Flow File=f09
Subcritical Flow
K Sum by GR= 0
Std Step Tol= 0.01
Critical Tol= 0.01
Num of Std Step Trials= 20
Max Error Tol= 0.3
Flow Tol Ratio= 0.001
Split Flow NTrial= 30
Split Flow Tol= 0.02
Split Flow Ratio= 0.02
Log Output Level= 0
Friction Slope Method= 1
Unsteady Friction Slope Method= 2
Unsteady Bridges Friction Slope Method= 1
Parabolic Critical Depth
Global Vel Dist= 0 , 0 , 0
Global Log Level= 0
CheckData=True
Encroach Param=-1 ,0,0, 2
Encroach River=K166-00-00
Encroach Reach=K166-00-00_0008
Encroach Node=45151.3
       1 4127.55 5622.63
Encroach Node=45058.4
       1 4127.55 5622.63
Encroach Node=45016.4
       1 4127.55 5622.63
Encroach Node=44908.9
       1 4164.42 5622.63
Encroach Node=43670.8
       1  4487.6 5414.83
Encroach Node=42728.2
       1 4562.99 5280.95
Encroach Node=41549.3
       1  4082.9 5072.73
Encroach Node=40725.8
       1 4557.07 5642.15
Encroach Node=39922.5
       1 4606.45 5340.71
Encroach Node=38467.1
       1 4668.18 5776.18
Encroach Node=37472.8
       1 4623.35 5799.05
Encroach Node=36436.4
       1  4275.9 5282.51
Encroach Node=35353.3
       1 4639.13  5407.1
Encroach Node=34255.2
       1  4973.6 5805.59
Encroach Node=33232.8
       1 4873.33 6201.16
Encroach Node=32250.4
       1 4501.56  5410.3
Encroach Node=31285.5
       1 4219.75 5344.76
Encroach Node=31160.1
       1 4219.75 5344.76
Encroach Node=31131.1
       1 4195.16 5342.23
Encroach Node=30982.6
       1 3935.16 5342.23
Encroach Node=30396.4
       1  3690.2  5042.9
Encroach Node=30280.1
       1  3660.2  5042.9
Encroach Node=30220.1
       1  3660.2  5042.9
Encroach Node=30112.8
       1  3660.2 5043.04
Encroach Node=28594.3
       1    3990  5392.8
Encroach Node=28002.4
       1 4392.66    5700
Encroach Node=26583.9
       1 4922.88 6294.99
Encroach Node=25409.3
       1 4620.65 6066.57
Encroach Node=24776.4
       1 4673.07 5907.49
Encroach Node=23735.9
       1  4963.5 6784.89
Encroach Node=22653.9
       1    4952 6323.72
Encroach Node=21483.3
       1  4752.7  6302.1
Encroach Node=20611.8
       1 4535.91 6335.88
Encroach Node=19746.9
       1 4326.03 5834.55
Encroach Node=18798.2
       1 4926.63  6415.9
Encroach Node=17908.8
       1 4447.31 5924.02
Encroach Node=16703.7
       1 4716.43  6074.8
Encroach Node=15856.6
       1  4947.7 6973.68
Encroach Node=14739.3
       1  4910.9 7091.81
Encroach Node=13584.7
       1  4935.3 8323.28
Encroach Node=12699.3
       1  4951.1  8058.6
Encroach Node=11631.6
       1 4821.33 7722.07
Encroach Node=10235.0
       1  4973.8 7833.25
Encroach Node=9299.0
       1  4925.3 8464.06
Encroach Node=8221.7
       1  4981.4 8992.98
Encroach Node=7093.1
       1    4889 8875.21
Encroach Node=6027.2
       1  4962.5  9406.1
Encroach Node=4958.5
       1  4966.1    9423
Encroach Node=3940.8
       1  4954.6  8646.4
Encroach Node=2871.2
       1    4891 7845.93
Encroach Node=1778.7
       1  4956.6 7517.66
Encroach Node=795.9
       1 3703.58 7473.69
BEGIN DESCRIPTION:
FEMA Effective Floodway October 2013
Flows based on the revised Modified-Puls data in conjunction with the Cypress Creek LOMR.
END DESCRIPTION:
Computation Interval=1HOUR
Output Interval=1HOUR
Run HTab= 0
Run UNet= 0
Run PostProcess= 0
UNET Theta= 1
UNET Theta Warmup= 1
UNET ZTol= 0.02
UNET ZSATol= 0.1
UNET MxIter= 20
UNET MaxInSteps= 20
UNET DtIC= 0
UNET DtMin= 0
UNET MaxCRTS= 20
UNET WFStab= 2
UNET SFStab= 1
UNET WFX= 1
UNET SFX= 1
UNET DSS MLevel= 4
UNET DZMax Abort= 100
UNET Convert EG Bridges=-1
UNET Use Existing IB Tables=-1
UNET Froude Reduction=False
UNET Froude Limit= 1
UNET Froude Power= 10
Instantaneous Interval=1HOUR
Write IC File= 0
IC Time=0,,
Echo Input=False
Echo Output=False
Write Detailed= 0
Detailed Automatic Start=False, 10

--- K166-00-00.p03 (plan) ---

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Plan Title=Effective MP 2013
Short Identifier=Eff MP 2013
Geom File=g01
Flow File=f08
Encroach Param=-1 ,0,0, 0
FEMA Effective MP October 2013

--- K166-00-00.f09 (steady flow) ---

Flow Title=Effective FW 2013
Program Version=3.13
Number of Profiles= 2
Profile Names=1PCT_100yr,1PCTFloodway_10
River Rch & RM=K166-00-00,K166-00-00_0008       ,45151.3
    2760    2760
River Rch & RM=K166-00-00,K166-00-00_0008       ,44908.9
    3052    3052
River Rch & RM=K166-00-00,K166-00-00_0008       ,43670.8
   10340   10340
River Rch & RM=K166-00-00,K166-00-00_0008       ,42728.2
   11010   11010
River Rch & RM=K166-00-00,K166-00-00_0008       ,35353.3
   11616   11616
River Rch & RM=K166-00-00,K166-00-00_0008       ,28002.4
   14440   14440
River Rch & RM=K166-00-00,K166-00-00_0008       ,16703.7
   14967   14967
River Rch & RM=K166-00-00,K166-00-00_0008       ,795.9
   15740   15740
Boundary for River Rch & Prof#=K166-00-00,K166-00-00_0008       , 1
Up Type= 0
Dn Type= 3
Dn Slope=0.01
Boundary for River Rch & Prof#=K166-00-00,K166-00-00_0008       , 2
Up Type= 0
Dn Type= 3
Dn Slope=0.01
DSS Import GetInterval= 0
DSS Import GetPeak= 0
DSS Import FillOption= 0

--- K166-00-00.f08 (steady flow) ---

Flow Title=Effectve MP 2013
Program Version=3.13
Number of Profiles= 4
Profile Names=10PCT_10yr,2PCT_50yr,1PCT_100yr,0.2PCT_500yr
River Rch & RM=K166-00-00,K166-00-00_0008       ,45151.3
    1159    2344    2760    3993
River Rch & RM=K166-00-00,K166-00-00_0008       ,44908.9
    1656    2593    3052    4437
River Rch & RM=K166-00-00,K166-00-00_0008       ,43670.8
    5166    8561   10340   15543
River Rch & RM=K166-00-00,K166-00-00_0008       ,42728.2
    5468    9106   11010   16594
River Rch & RM=K166-00-00,K166-00-00_0008       ,35353.3
    5689    9586   11616   17612
River Rch & RM=K166-00-00,K166-00-00_0008       ,28002.4
    6583   11679   14440   22348
River Rch & RM=K166-00-00,K166-00-00_0008       ,16703.7
    6770   12065   14967   23301
River Rch & RM=K166-00-00,K166-00-00_0008       ,795.9
    7040   12629   15740   24708
Boundary for River Rch & Prof#=K166-00-00,K166-00-00_0008       , 1
Up Type= 0
Dn Type= 3
Dn Slope=0.01
Boundary for River Rch & Prof#=K166-00-00,K166-00-00_0008       , 2
Up Type= 0
Dn Type= 3
Dn Slope=0.01
Boundary for River Rch & Prof#=K166-00-00,K166-00-00_0008       , 3
Up Type= 0
Dn Type= 3
Dn Slope=0.01
Boundary for River Rch & Prof#=K166-00-00,K166-00-00_0008       , 4
Up Type= 0
Dn Type= 3
Dn Slope=0.01
DSS Import GetInterval= 0
DSS Import GetPeak= 0
DSS Import FillOption= 0

--- K166-00-00.g01 (geometry) ---

Geom Title=K166-00-00 2013
Program Version=3.13

River Reach=K166-00-00      ,K166-00-00_0008
Reach XY= 30
      2940261.04     13937459.49      2942254.74     13934477.98
      2942148.43     13933883.23       2943019.1     13933233.48
      2942870.97     13932878.73      2943600.32     13932120.64
      2944373.08       13930295.      2947122.08     13928615.62
      2946790.08       13927374.      2946973.64     13926005.38
      2948929.33       13924940.      2949766.26     13925591.54
      2950391.72     13923847.54      2951464.58       13922862.
      2951375.83       13921098.      2952250.83       13919254.
       2951511.1     13917993.67      2951774.33       13917185.
      2952463.58       13917102.      2951876.08       13916357.
      2952552.83       13915503.      2951997.08       13915210.
      2951434.58       13913694.      2953244.24     13912634.93
      2953260.58       13911704.      2954156.58       13910808.
      2953896.08       13910103.      2952197.33       13908996.
      2952907.83       13907129.        2952616.       13906049.

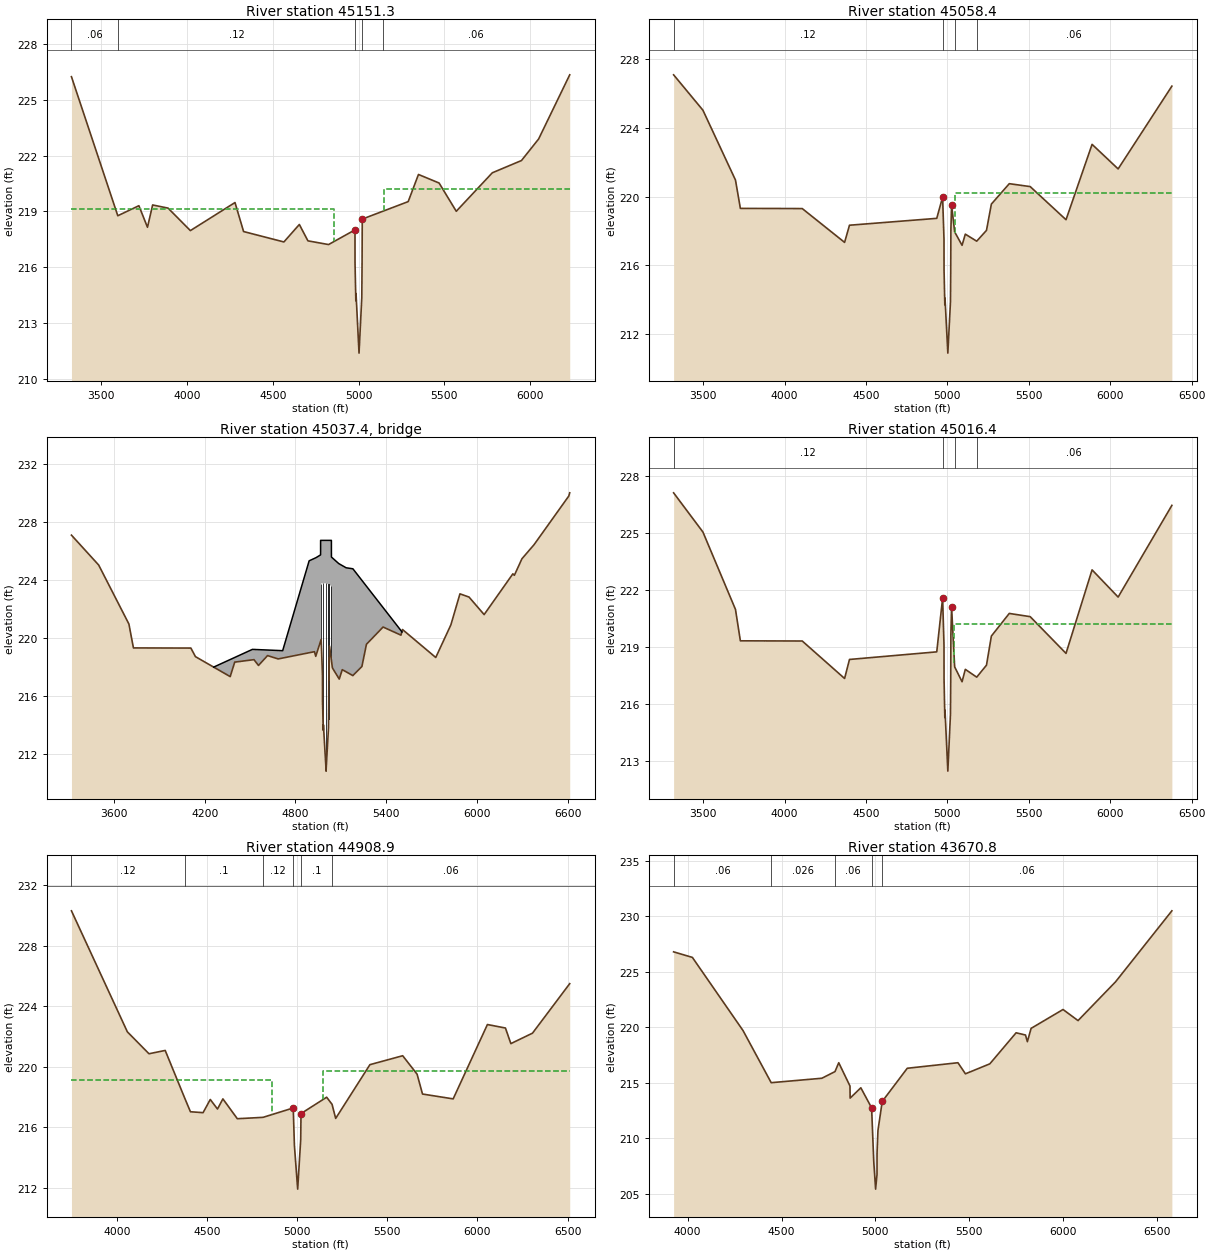
Type RM Length L Ch R = 1 ,45151.3 ,91,92.9,96
BEGIN DESCRIPTION:
Penick - XS4
END DESCRIPTION:
XS GIS Cut Line= 6
      2940330.22     13938292.35      2940282.65     13937962.74
      2940536.26     13937094.14      2940554.49      13936834.6
      2940564.69     13936270.52      2939796.73     13935927.32
#Sta/Elev= 30
  3327.1  226.24  3597.1  218.76  3720.1   219.3  3770.1  218.14  3800.1  219.34
  3890.1  219.17  4020.1  217.96  4280.1  219.47  4330.1  217.91    4565  217.35
    4655  218.29    4705  217.41  4825.2  217.21  4979.2     218  4979.5  216.23
  4984.2  214.19  4985.4  214.57  5002.8  211.37  5018.9  214.36  5020.5  216.19
  5021.6  218.58    5140 218.996  5289.2  219.52  5349.2  220.98  5469.4  220.52
  5569.4     219  5779.4  221.07  5949.4  221.73  6049.4  222.89  6230.5  226.34
#Mann= 5 ,-1 , 0
  3327.1     .06       0  3597.1     .12       0  4979.2     .08       0
  5021.6      .1       0    5140     .06       0
#XS Ineff= 2 , 0
       0  4854.3  219.13  5146.8       0   220.2
Permanent Ineff=
       F       F
Bank Sta=4979.2,5021.6
Exp/Cntr=0.5,0.3

Type RM Length L Ch R = 1 ,45058.4 ,43,42,41
BEGIN DESCRIPTION:
Penick - XS3
END DESCRIPTION:
XS GIS Cut Line= 6
      2940369.14      13938282.3      2940555.25      13937340.9
      2940621.71      13937101.9      2940642.83      13936693.7
      2940656.15      13936130.1      2939854.88      13935766.2
#Sta/Elev= 30
  3318.8   227.1  3498.8  225.04  3698.8  220.97  3728.8  219.32  4108.8  219.31
  4368.8  217.34  4398.8  218.34  4934.7  218.74  4970.7  219.98  4979.2  217.52
  4979.5  215.75  4984.2  213.71  4985.4  214.09  5002.8  210.89  5018.9  213.88
  5020.5  215.71  5021.6   218.1  5025.7  219.52  5044.7  217.95  5090.1  217.17
  5110.1  217.82  5180.1  217.41  5240.1  218.04  5270.1  219.57  5380.1  220.76
  5508.5  220.59  5728.5  218.66  5888.5  223.05  6048.5  221.62  6378.5  226.44
#Mann= 4 ,-1 , 0
  3318.8     .12       0  4970.7     .08       0  5044.7      .1       0
  5180.1     .06       0
#XS Ineff= 2 , 0
       0  4954.3  219.13  5046.8       0   220.2
Permanent Ineff=
       F       F
Bank Sta=4970.7,5025.7
Exp/Cntr=0.5,0.3

Type RM Length L Ch R = 3 ,45037.4 ,,,
BEGIN DESCRIPTION:
PENICK ROAD
Structure ID: K166-00-00-S2
END DESCRIPTION:
Bridge Culvert--1,0,-1,-1, 0
Deck Dist Width WeirC Skew NumUp NumDn MinLoCord MaxHiCord MaxSubmerge Is_Ogee
10,22,3,0, 37, 37, , , 0.95, 0, 1,1,,
    4260  4515.8  4715.8    4891    4937 4966.69  4966.8 4966.91 4968.71  4968.8
  4969.5  4969.8  4970.7  4979.2  4979.5  4984.2  4985.4  5001.7  5002.8    5004
  5018.9  5020.5  5021.6  5025.7  5036.4  5036.8  5036.9 5036.99  5037.1 5038.19
  5038.3 5038.41  5086.7  5135.5  5180.4  5496.7    5505
     218  219.22  219.13  225.33  225.55  225.74  226.74  226.74  226.74  226.74
  226.74  226.74  226.74  226.74  226.74  226.74  226.74  226.74  226.74  226.74
  226.74  226.74  226.74  226.74  226.74  226.74  226.74  226.74  226.74  226.74
  226.74  225.59  225.14  224.85  224.78  220.54  220.42
                                                                  219.91  223.75
  223.76  223.76  223.76  223.77  223.77  223.77  223.77  223.78  223.78  223.78
   223.7  223.69  223.68  223.66   223.6   223.6   223.6   223.6
                                                        
    4260  4515.8  4715.8    4891    4937 4966.69  4966.8 4966.91 4968.71  4968.8
  4969.5  4969.8  4970.7  4979.2  4979.5  4984.2  4985.4  5001.7  5002.8    5004
  5018.9  5020.5  5021.6  5025.7  5036.4  5036.8  5036.9 5036.99  5037.1 5038.19
  5038.3 5038.41  5086.7  5135.5  5180.4  5496.7    5505
     218  219.22  219.13  225.33  225.55  225.74  226.74  226.74  226.74  226.74
  226.74  226.74  226.74  226.74  226.74  226.74  226.74  226.74  226.74  226.74
  226.74  226.74  226.74  226.74  226.74  226.74  226.74  226.74  226.74  226.74
  226.74  225.59  225.14  224.85  224.78  220.54  220.42
                                                                  219.91  223.75
  223.76  223.76  223.76  223.77  223.77  223.77  223.77  223.78  223.78  223.78
   223.7  223.69  223.68  223.66   223.6   223.6   223.6   223.6
                                                        
Pier Skew, UpSta & Num, DnSta & Num=  ,4969.8, 2 ,4969.8, 2 , 0 , 0 , 0 ,,
       1       1
  218.58  224.76
       1       1
  220.28  226.46
Pier Skew, UpSta & Num, DnSta & Num=  ,4985.4, 2 ,4985.4, 2 , 0 , 0 , 0 ,,
       1       1
  212.86  224.77
       1       1
  214.56  226.47
Pier Skew, UpSta & Num, DnSta & Num=  ,5002.8, 2 ,5002.8, 2 , 0 , 0 , 0 ,,
       1       1
  209.91  224.78
       1       1
  211.61  226.48
Pier Skew, UpSta & Num, DnSta & Num=  ,5019.4, 2 ,5019.4, 2 , 0 , 0 , 0 ,,
       1       1
  212.81   224.7
       1       1
  214.51   226.4
Pier Skew, UpSta & Num, DnSta & Num=  ,5036.4, 2 ,5036.4, 2 , 0 , 0 , 0 ,,
       1       1
  220.29   224.6
       1       1
  221.99   226.3
Abutment Skew #Up #Dn= , 5 , 5
  5025.7  5036.4  5036.8  5036.9 5036.99
  219.52  221.45  221.93  222.05  222.05
  5025.7  5036.4  5036.8  5036.9 5036.99
  221.15  223.08  223.56  223.68  223.68
BR Coef= 1 , 1 , 1 ,1.25, 0 ,,,0.8,-1,2,0,
WSPro=,,,, 1 ,,,, 0 ,,,, 0 ,,,,-1 ,-1 ,-1 , 0 , 0 , 0 , 0 , 0
BR U #Sta/Elev= 47
  3318.8   227.1  3498.8  225.04  3698.8  220.97  3728.8  219.32  4108.8  219.31
  4138.8  218.72  4368.8  217.34  4398.8  218.34    4526  218.51    4556  218.11
    4616  218.79    4686  218.56    4926  219.06  4934.7  218.74  4970.7  219.91
  4979.2  217.45  4979.5  215.68  4984.2  213.64  4985.4  214.02  5001.7  211.13
  5002.8  210.82    5004  211.04  5018.9  213.81  5020.5  215.64  5021.6  218.03
  5025.7  219.45  5044.7  217.95  5050.1  217.85  5090.1  217.17  5110.1  217.82
  5180.1  217.41  5240.1  218.04  5270.1  219.57  5380.1  220.76  5498.5   220.2
  5508.5  220.59  5728.5  218.66  5828.5  220.91  5888.5  223.05  5948.5  222.83
  6048.5  221.62  6238.5  224.43  6248.5  224.33  6298.5  225.47  6378.5  226.44
  6608.5   229.8  6614.6  230.02
BR U #Mann= 4
  3318.8     .12  4970.7     .08  5044.7      .1  5180.1     .06
BR U Banks=4970.7,5025.7
BR D #Sta/Elev= 47
  3318.8   227.1  3498.8  225.04  3698.8  220.97  3728.8  219.32  4108.8  219.31
  4138.8  218.72  4368.8  217.34  4398.8  218.34    4526  218.51    4556  218.11
    4616  218.79    4686  218.56    4926  219.06  4934.7  218.74  4970.7  221.61
  4979.2  219.15  4979.5  217.38  4984.2  215.34  4985.4  215.72  5001.7  212.83
  5002.8  212.52    5004  212.74  5018.9  215.51  5020.5  217.34  5021.6  219.73
  5025.7  221.15  5044.7  217.95  5050.1  217.85  5090.1  217.17  5110.1  217.82
  5180.1  217.41  5240.1  218.04  5270.1  219.57  5380.1  220.76  5498.5   220.2
  5508.5  220.59  5728.5  218.66  5828.5  220.91  5888.5  223.05  5948.5  222.83
  6048.5  221.62  6238.5  224.43  6248.5  224.33  6298.5  225.47  6378.5  226.44
  6608.5   229.8  6614.6  230.02
BR D #Mann= 4
  3318.8     .12  4970.7     .08  5044.7      .1  5180.1     .06
BR D Banks=4970.7,5025.7
BC Design=,, 0 ,, 0 ,,,,,,
BC HTab HWMax=230.07

Type RM Length L Ch R = 1 ,45016.4 ,220,107.5,96
BEGIN DESCRIPTION:
Penick - XS2
END DESCRIPTION:
XS GIS Cut Line= 6
      2940382.41     13938284.49      2940569.36     13937355.03
      2940667.42      13937099.4      2940688.57     13936690.72
      2940701.98     13936123.82      2939897.68     13935758.55
#Sta/Elev= 30
  3318.8   227.1  3498.8  225.04  3698.8  220.97  3728.8  219.32  4108.8  219.31
  4368.8  217.34  4398.8  218.34  4934.7  218.74  4970.7  221.56  4979.2   219.1
  4979.5  217.33  4984.2  215.29  4985.4  215.67  5002.8  212.47  5018.9  215.46
  5020.5  217.29  5021.6  219.68  5025.7   221.1  5044.7  217.95  5090.1  217.17
  5110.1  217.82  5180.1  217.41  5240.1  218.04  5270.1  219.57  5380.1  220.76
  5508.5  220.59  5728.5  218.66  5888.5  223.05  6048.5  221.62  6378.5  226.44
#Mann= 4 ,-1 , 0
  3318.8     .12       0  4970.7     .08       0  5044.7      .1       0
  5180.1     .06       0
#XS Ineff= 2 , 0
       0 4957.63  219.13 5043.47       0   220.2
Permanent Ineff=
       F       F
Bank Sta=4970.7,5025.7
Exp/Cntr=0.5,0.3

Type RM Length L Ch R = 1 ,44908.9 ,1125.6,1238.1,1249.1
BEGIN DESCRIPTION:
Penick - XS1
END DESCRIPTION:
XS GIS Cut Line= 6
      2941437.98     13937636.53      2940782.16     13936800.62
      2940788.71     13936633.15      2940788.71     13936517.71
      2940802.12     13936066.25      2939922.46     13935665.67
#Sta/Elev= 30
  3747.9  230.29  4057.9   222.3  4177.9  220.85  4267.9  221.07  4377.9  217.87
  4407.9  217.02  4477.9  216.96  4517.9  217.83  4557.9   217.2  4587.9  217.87
  4667.9  216.56  4810.4  216.65    4978  217.27 4984.59  214.79 5002.69  211.91
 5019.49  215.19 5021.16   216.9  5163.4  217.98  5193.4  217.51  5213.4  216.58
  5403.4  220.13  5585.1  220.72  5665.1   219.5  5695.1  218.19  5865.1  217.87
  6055.1  222.78  6155.1  222.55  6185.1  221.52  6305.1  222.21  6511.6  225.48
#Mann= 6 ,-1 , 0
  3747.9     .12       0  4377.9      .1       0  4810.4     .12       0
    4978     .08       0 5021.16      .1       0  5193.4     .06       0
#XS Ineff= 2 , 0
       0 4857.63  219.13 5143.47       0   219.7
Permanent Ineff=
       F       F
Bank Sta=4978,5021.16
Exp/Cntr=0.3,0.1

Type RM Length L Ch R = 1 ,43670.8 ,941.6,942.6,943.6
BEGIN DESCRIPTION:
Cross Section K166-00-00-X39
END DESCRIPTION:
XS GIS Cut Line= 4
 2942469.005582913935905.8106498      2941573.65     13935695.24
       2941307.1     13935508.66 2939972.407573713935054.2814143
#Sta/Elev= 30
    3925   226.8    4025   226.3    4295   219.7    4445     215    4715   215.4
    4785     216    4805   216.8  4864.8   214.7  4865.7  213.61  4922.7  214.54
  4980.1  212.73  4991.5   207.9  5001.4   205.4  5008.9  206.73    5009  208.32
  5009.2  208.71  5013.9  210.69  5036.8  213.31  5170.1   216.3  5440.1   216.8
  5480.1   215.8  5610.1   216.7  5750.1   219.5  5800.1   219.3  5810.1   218.7
  5830.1   219.9  6000.1   221.6  6080.1   220.6  6280.1   224.1  6580.1   230.5
#Mann= 5 ,-1 , 0
    3925     .06       0    4445    .026       0    4785     .06       0
  4980.1     .12       0  5036.8     .06       0
#Block Obstruct= 2 , 0
         4785.12     216
Bank Sta=4980.1,5036.8
Exp/Cntr=0.3,0.1

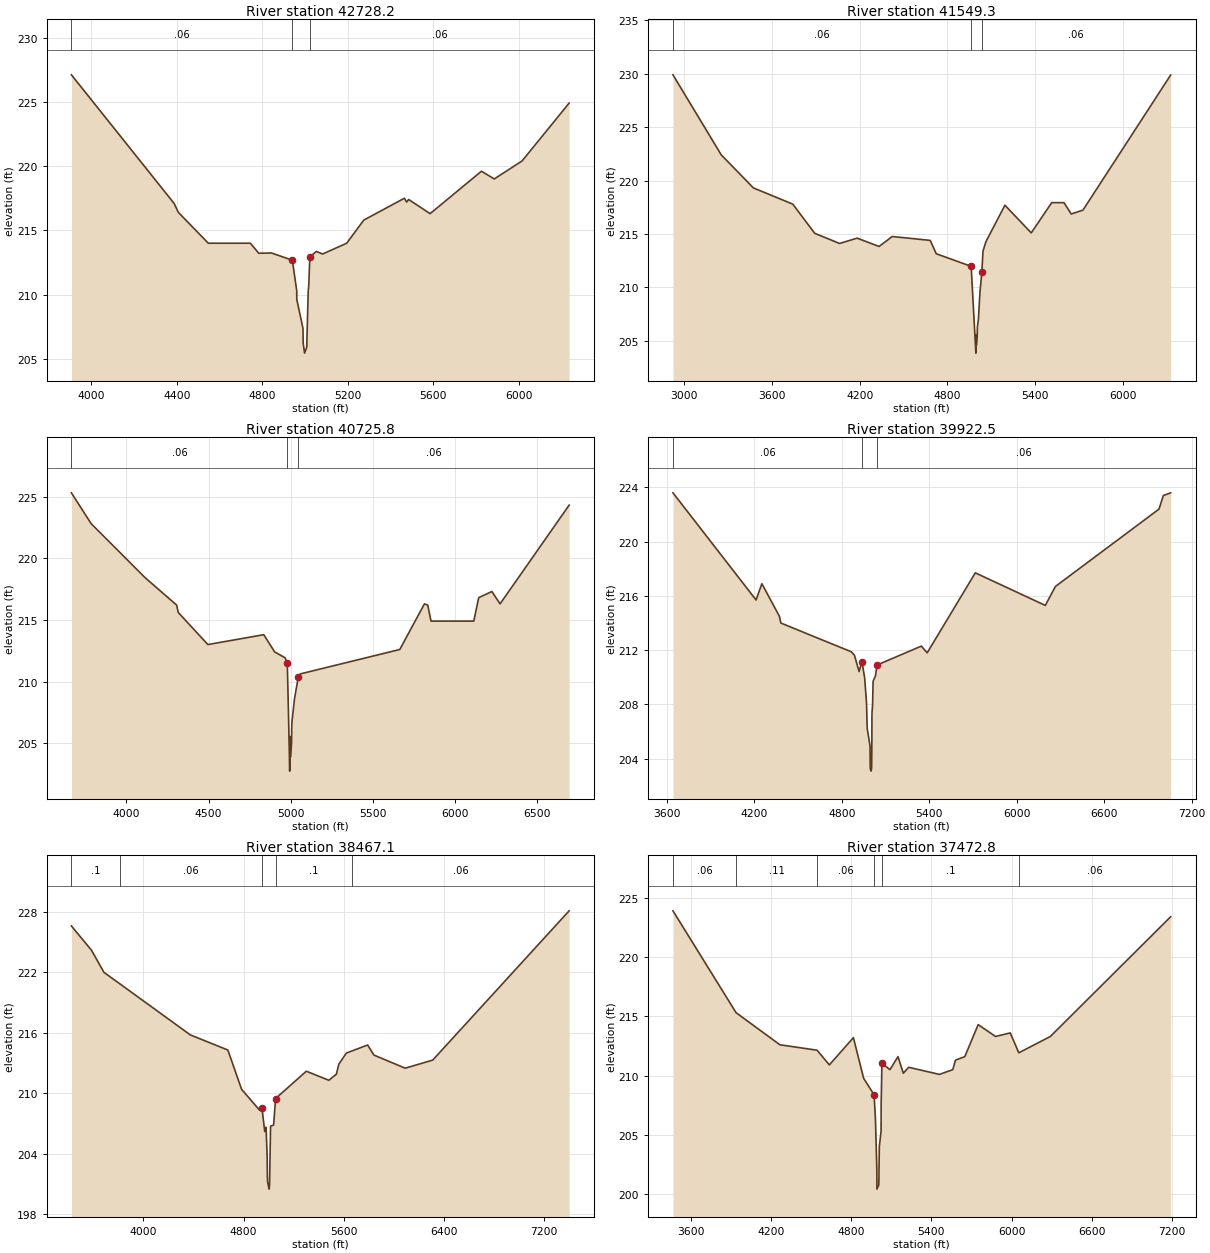
Type RM Length L Ch R = 1 ,42728.2 ,1253.58,1179.2,852.97
BEGIN DESCRIPTION:
Cross Section K166-00-00-X38
END DESCRIPTION:
XS GIS Cut Line= 4
      2942534.86     13935683.61      2942088.97     13934975.57
      2941795.77     13934717.91 2940964.928765213933996.9440247
#Sta/Elev= 30
  3907.7   227.1  4387.7   217.1  4407.7   216.4  4547.7     214  4744.4     214
  4783.6  213.22    4843  213.24  4940.8  212.68  4961.2   210.3  4961.4  209.63
  4990.4  207.37  4991.2  206.24  4997.8  205.45  5008.3  205.93  5009.2  206.79
  5014.9  210.27  5017.4  210.71  5022.4  212.94  5053.1  213.36  5082.3  213.16
  5194.8     214  5274.8   215.8  5464.8   217.5  5474.8   217.2  5484.8   217.4
  5584.8   216.3  5824.8   219.6  5884.8     219  6014.8   220.4  6234.8   224.9
#Mann= 3 ,-1 , 0
  3907.7     .06       0  4940.8     .08       0  5022.4     .06       0
Bank Sta=4940.8,5022.4
Exp/Cntr=0.3,0.1

Type RM Length L Ch R = 1 ,41549.3 ,409.08,823.2,441.03
BEGIN DESCRIPTION:
Cross Section K166-00-00-interpolatedxs -2
END DESCRIPTION:
XS GIS Cut Line= 4
 2944196.916417813934210.0382637      2942458.03     13933937.86
      2941576.98      13933946.1 2940845.849982913933725.5982339
#Sta/Elev= 30
  2922.9  229.89  3252.9  222.41  3472.9  219.31  3742.9  217.79  3892.9  215.06
  4062.9  214.11  4182.9  214.61  4332.9  213.83  4422.9  214.76  4682.9   214.4
    4724  213.15 4963.06  211.97 4995.15  203.85 4996.48  205.52 4997.27  204.57
 4999.77  204.59 5003.77   205.3  5005.8  206.33 5012.54  207.01 5023.47  209.62
 5035.89  211.41    5044  213.39    5064  214.28    5194  217.69    5374   215.1
    5514  217.93  5597.7  217.93  5647.7  216.87  5727.7  217.23  6327.7  229.87
#Mann= 3 ,-1 , 0
  2922.9     .06       0 4963.06     .08       0 5035.89     .06       0
Bank Sta=4963.06,5035.89
Exp/Cntr=0.3,0.1

Type RM Length L Ch R = 1 ,40725.8 ,802,803.3,804
BEGIN DESCRIPTION:
Cross Section K166-00-00-X37
END DESCRIPTION:
XS GIS Cut Line= 4
 2944067.533236913933946.4788767      2942863.77     13933589.25
       2942762.8     13933521.36 2941113.924795113933581.0219739
#Sta/Elev= 30
  3665.5   225.3  3785.5   222.8  4115.5   218.4  4305.5   216.2  4315.5   215.6
  4495.5     213  4835.5   213.8  4901.8   212.4  4965.1  211.93  4978.6  211.47
  4984.9  207.93  4993.3  202.74    4995  205.54    4996  203.92  4999.2   203.9
  5004.3  205.03  5005.6  206.39  5006.9  206.74  5022.8  208.65  5045.3  210.35
  5057.2  210.62  5662.8   212.6  5812.8   216.3  5832.8   216.2  5852.8   214.9
  6112.8   214.9  6142.8   216.8  6222.8   217.3  6272.8   216.3  6692.8   224.3
#Mann= 3 ,-1 , 0
  3665.5     .06       0  4978.6     .08       0  5045.3     .06       0
Bank Sta=4978.6,5045.3
Exp/Cntr=0.3,0.1

Type RM Length L Ch R = 1 ,39922.5 ,1299.97,1455.4,1412.89
BEGIN DESCRIPTION:
Cross Section K166-00-00-X36
END DESCRIPTION:
XS GIS Cut Line= 4
 2944958.473960713934034.0807273      2942956.11      13932943.7
      2942823.83      13932887.2 2939173.071136813933111.9058191
#Sta/Elev= 30
  3641.7   223.6  4211.7   215.7  4251.7   216.9  4371.7   214.5  4381.7     214
  4864.8  211.88  4886.5  211.63  4918.4  210.42  4937.6  211.16  4956.3  209.99
  4969.4  208.12  4974.3  206.22  4993.4  204.95    4995  203.28    5001  203.08
  5004.5  203.32  5005.7  204.52  5006.7  207.34  5010.8  207.92  5014.6  209.71
    5031  210.11  5041.1   210.9  5345.5   212.3  5385.5   211.8  5715.5   217.7
  6195.5   215.3  6265.5   216.7  6975.5   222.4  7005.5   223.4  7055.5   223.6
#Mann= 3 ,-1 , 0
  3641.7     .06       0  4937.6     .08       0  5041.1     .06       0
#XS Ineff= 2 , 0
                          5715.5           217.7
Permanent Ineff=
       F       F
Bank Sta=4937.6,5041.1
Exp/Cntr=0.3,0.1

Type RM Length L Ch R = 1 ,38467.1 ,855.99,994.3,846
BEGIN DESCRIPTION:
Cross Section K166-00-00-X35
END DESCRIPTION:
XS GIS Cut Line= 4
  2945009.94843913932573.1090904      2943671.28     13931855.54
      2943550.74     13931812.27 2941550.028053613930618.0927125
#Sta/Elev= 30
  3424.4   226.6  3584.4   224.2  3684.4     222  3816.2  220.82  4374.4   215.8
  4674.4   214.3  4784.4   210.4  4928.5  208.33  4947.2  208.56  4969.1  206.22
  4979.8  206.65  4988.6  203.69    4990  201.81  4992.2  201.19  5004.4  200.51
  5007.6  200.95  5015.7  206.75  5039.8  206.86  5055.8  209.49  5301.3   212.2
  5481.3   211.3  5541.3   211.9  5561.3   212.9  5621.3     214  5666.5  214.21
  5791.3   214.8  5841.3   213.8  6091.3   212.5  6311.3   213.3  7401.3   228.1
#Mann= 5 ,-1 , 0
  3424.4      .1       0  3816.2     .06       0  4947.2     .08       0
  5055.8      .1       0  5666.5     .06       0
Bank Sta=4947.2,5055.8
Exp/Cntr=0.3,0.1

Type RM Length L Ch R = 1 ,37472.8 ,1011.41,1036.4,1096.68
BEGIN DESCRIPTION:
Cross Section K166-00-00-X34
END DESCRIPTION:
XS GIS Cut Line= 4
 2945157.9804074 13932107.914636      2944169.32     13931056.29
      2944070.03     13931043.34 2941967.142370913930468.7290639
#Sta/Elev= 30
  3466.8   223.9  3938.8  215.31  4266.8   212.6  4545.1  212.14  4636.8   210.9
  4816.8   213.2  4893.5  209.77  4971.5  208.38  4981.6  206.39    4992  202.15
  4992.7  200.42  5006.8  200.77  5010.8  204.01    5024  205.31 5024.11  207.41
  5030.2  211.04  5090.3   210.5  5150.3   211.6  5190.3   210.2  5230.3   210.7
  5460.3   210.1  5560.3   210.5  5580.3   211.3  5650.3   211.6  5750.3   214.3
  5880.3   213.3  5990.3   213.6  6054.3  211.92  6290.3   213.3  7190.3   223.4
#Mann= 6 ,-1 , 0
  3466.8     .06       0  3938.8     .11       0  4545.1     .06       0
  4971.5     .08       0  5030.2      .1       0  6054.3     .06       0
Bank Sta=4971.5,5030.2
Exp/Cntr=0.3,0.1

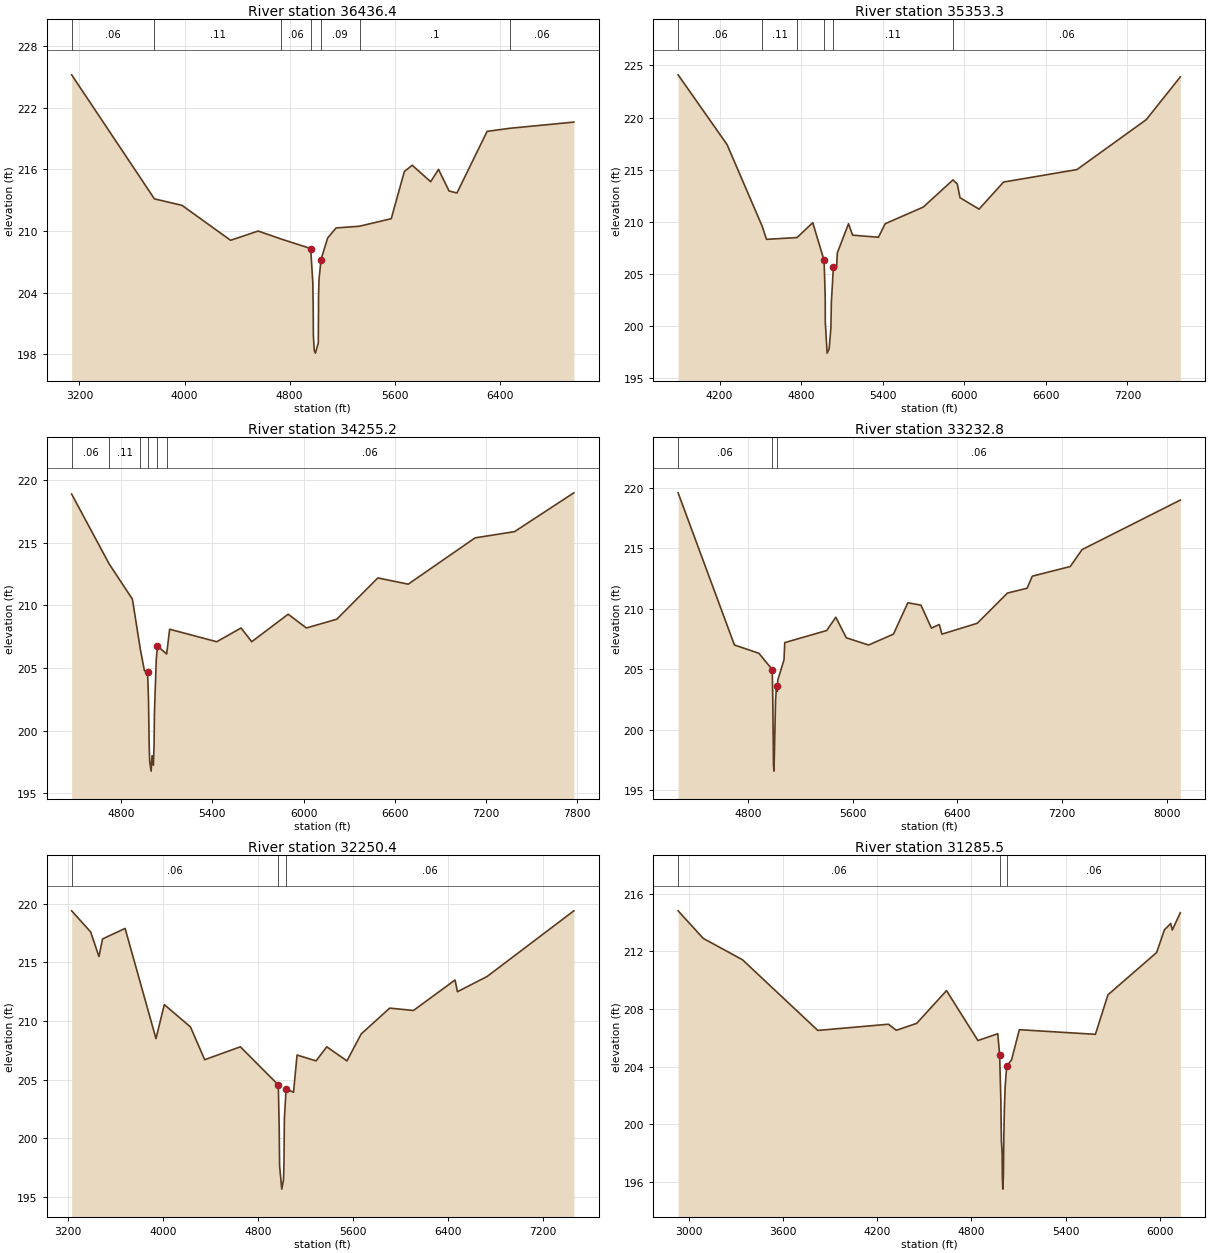
Type RM Length L Ch R = 1 ,36436.4 ,829.78,1083.1,1043.57
BEGIN DESCRIPTION:
Cross Section K166-00-00-X33
END DESCRIPTION:
XS GIS Cut Line= 4
  2946250.62844313930856.7474239       2944568.3     13930202.69
      2944509.31     13930100.43 2942609.408824613930093.3219882
#Sta/Elev= 30
  3140.9   225.2  3771.2  213.13  3980.9   212.5  4350.9   209.1  4560.9     210
  4736.7  209.22  4960.5   208.3  4976.6  205.06  4979.6  202.81    4981  199.85
  4987.7  198.39  4996.5  198.12  5018.5  199.11  5020.1  202.24  5020.3  203.54
  5023.9  205.28  5039.3  207.23    5090  209.33  5153.9   210.3  5332.2  210.47
  5573.9   211.2  5673.9   215.8  5733.9   216.4  5873.9   214.8  5933.9     216
  6013.9   213.9  6073.9   213.7  6303.9   219.7  6478.2     220  6963.9   220.6
#Mann= 7 ,-1 , 0
  3140.9     .06       0  3771.2     .11       0  4736.7     .06       0
  4960.5     .08       0  5039.3     .09       0  5332.2      .1       0
  6478.2     .06       0
Bank Sta=4960.5,5039.3
Exp/Cntr=0.3,0.1

Type RM Length L Ch R = 1 ,35353.3 ,978.74,1098.1,754.42
BEGIN DESCRIPTION:
Cross Section K166-00-00-X32
END DESCRIPTION:
XS GIS Cut Line= 4
  2946408.186409 13930270.695505      2945526.06     13929715.14
      2945459.16     13929591.31 2943490.189531213928034.6223681
#Sta/Elev= 30
  3895.3   224.1  4255.3   217.4  4513.8  209.55  4545.3   208.3    4770  208.47
  4885.3   209.9  4968.8  206.28  4976.6  202.97  4977.4  202.27  4977.6  200.37
  4991.2  197.37    5006  197.77  5018.7  199.77  5022.5  202.31  5037.5  205.69
  5061.1  205.64  5066.1  206.99  5148.5   209.8  5178.5   208.7  5368.5   208.5
  5418.5   209.8  5698.5   211.4    5917  214.01  5948.5   213.6  5968.5   212.3
  6108.5   211.2  6288.5   213.8  6828.5     215  7338.5   219.8  7588.5   223.9
#Mann= 6 ,-1 , 0
  3895.3     .06       0  4513.8     .11       0    4770     .09       0
  4968.8     .08       0  5037.5     .11       0    5917     .06       0
Bank Sta=4968.8,5037.5
Exp/Cntr=0.3,0.1

Type RM Length L Ch R = 1 ,34255.2 ,890.58,1022.4,676.42
BEGIN DESCRIPTION:
Cross Section K166-00-00-X31
END DESCRIPTION:
XS GIS Cut Line= 4
 2946808.8899851 13929565.739914      2946498.72     13929232.92
       2946357.1     13929138.97 2943954.921234113927950.6116392
#Sta/Elev= 30
  4473.9   218.9  4721.7   213.3  4873.9   210.5  4925.3  206.54  4952.6   204.8
  4973.6  204.65  4979.4  202.63  4984.1  198.83  4987.5  197.54  4996.8  196.76
  5003.1  197.99  5011.8  197.24  5016.3  198.83  5018.7  201.38  5023.1  202.97
  5030.9  205.69  5038.7  206.76  5099.2  206.12  5118.8   208.1  5428.8   207.1
  5588.8   208.2  5658.8   207.1  5898.8   209.3  6018.8   208.2  6218.8   208.9
  6488.8   212.2  6688.8   211.7  7128.8   215.4  7388.8   215.9  7778.8     219
#Mann= 6 ,-1 , 0
  4473.9     .06       0  4721.7     .11       0  4925.3     .09       0
  4973.6     .08       0  5038.7     .09       0  5099.2     .06       0
Bank Sta=4973.6,5038.7
Exp/Cntr=0.3,0.1

Type RM Length L Ch R = 1 ,33232.8 ,523.92,982.4,715.19
BEGIN DESCRIPTION:
Cross Section K166-00-00-X30
END DESCRIPTION:
XS GIS Cut Line= 4
 2947632.235882113929140.4922102      2947193.25     13928687.65
      2947076.93     13928573.02 2944161.214061713927712.7366127
#Sta/Elev= 30
  4267.6   219.6  4697.6     207  4884.1  206.32  4986.4  204.97  4990.4  202.45
  4995.8  197.04  4999.7  196.56  5011.6  202.42  5018.9   203.6  5024.9  203.16
  5028.4   204.1  5076.1  205.77  5081.6   207.2  5401.6   208.2  5471.6   209.3
  5551.6   207.6  5721.6     207  5911.6   207.9  6021.6   210.5  6121.6   210.3
  6201.6   208.4  6261.6   208.7  6281.6   207.9  6551.6   208.8  6781.6   211.3
  6931.6   211.7  6971.6   212.7  7261.6   213.5  7351.6   214.9  8101.6     219
#Mann= 3 ,-1 , 0
  4267.6     .06       0  4986.4     .08       0  5018.9     .06       0
Bank Sta=4986.4,5018.9
Exp/Cntr=0.3,0.1

Type RM Length L Ch R = 1 ,32250.4 ,600,964.9,900
BEGIN DESCRIPTION:
Cross Section K166-00-00-X29
END DESCRIPTION:
XS GIS Cut Line= 4
 2947934.540412913929121.3578207      2947002.27     13927691.58
      2946852.71     13927710.83 2944498.008873313927441.4114177
#Sta/Elev= 30
  3232.6   219.4  3392.6   217.6  3462.6   215.5  3492.6     217  3682.6   217.9
  3942.6   208.5  4012.6   211.4  4232.6   209.5  4352.6   206.7  4652.6   207.8
  4972.4  204.55  4980.1  200.75  4983.1  197.66  5001.4  195.66  5016.1  196.46
  5019.9   197.8  5023.6   201.7  5038.3  204.23  5100.3  203.92  5130.3   207.1
  5290.3   206.6  5380.3   207.8  5550.3   206.6  5670.3   208.9  5910.3   211.1
  6110.3   210.9  6460.3   213.5  6480.3   212.5  6730.3   213.8  7460.3   219.4
#Mann= 3 ,-1 , 0
  3232.6     .06       0  4972.4     .08       0  5038.3     .06       0
Bank Sta=4972.4,5038.3
Exp/Cntr=0.3,0.1

Type RM Length L Ch R = 1 ,31285.5 ,107,125.4,56
BEGIN DESCRIPTION:
S1a_PRIVATE ROAD - XS4
END DESCRIPTION:
XS GIS Cut Line= 4
      2947896.39     13928689.64      2947161.89     13926886.93
      2946819.97     13926892.09      2945995.31     13926505.17
#Sta/Elev= 30
  2930.9   214.8  3090.9  212.89  3340.9  211.41  3820.9  206.51  4270.9  206.94
  4320.9  206.52  4450.9     207  4640.9  209.27  4840.9  205.81  4967.5  206.28
 4979.39  204.81 4986.91  201.76 4990.73  198.79 4995.39  197.99 4996.66  196.32
 4999.63  195.51 5003.48  196.53 5006.26  199.23 5009.68  201.12 5014.43  202.58
 5024.23  204.02 5055.32  204.47 5104.86  206.56  5589.5  206.24  5669.5  208.98
  5979.5  211.91  6029.5  213.49  6069.5  213.92  6079.5  213.47  6130.4  214.67
#Mann= 3 ,-1 , 0
  2930.9     .06       0 4979.39     .08       0 5024.23     .06       0
Bank Sta=4979.39,5024.23
Exp/Cntr=0.5,0.3

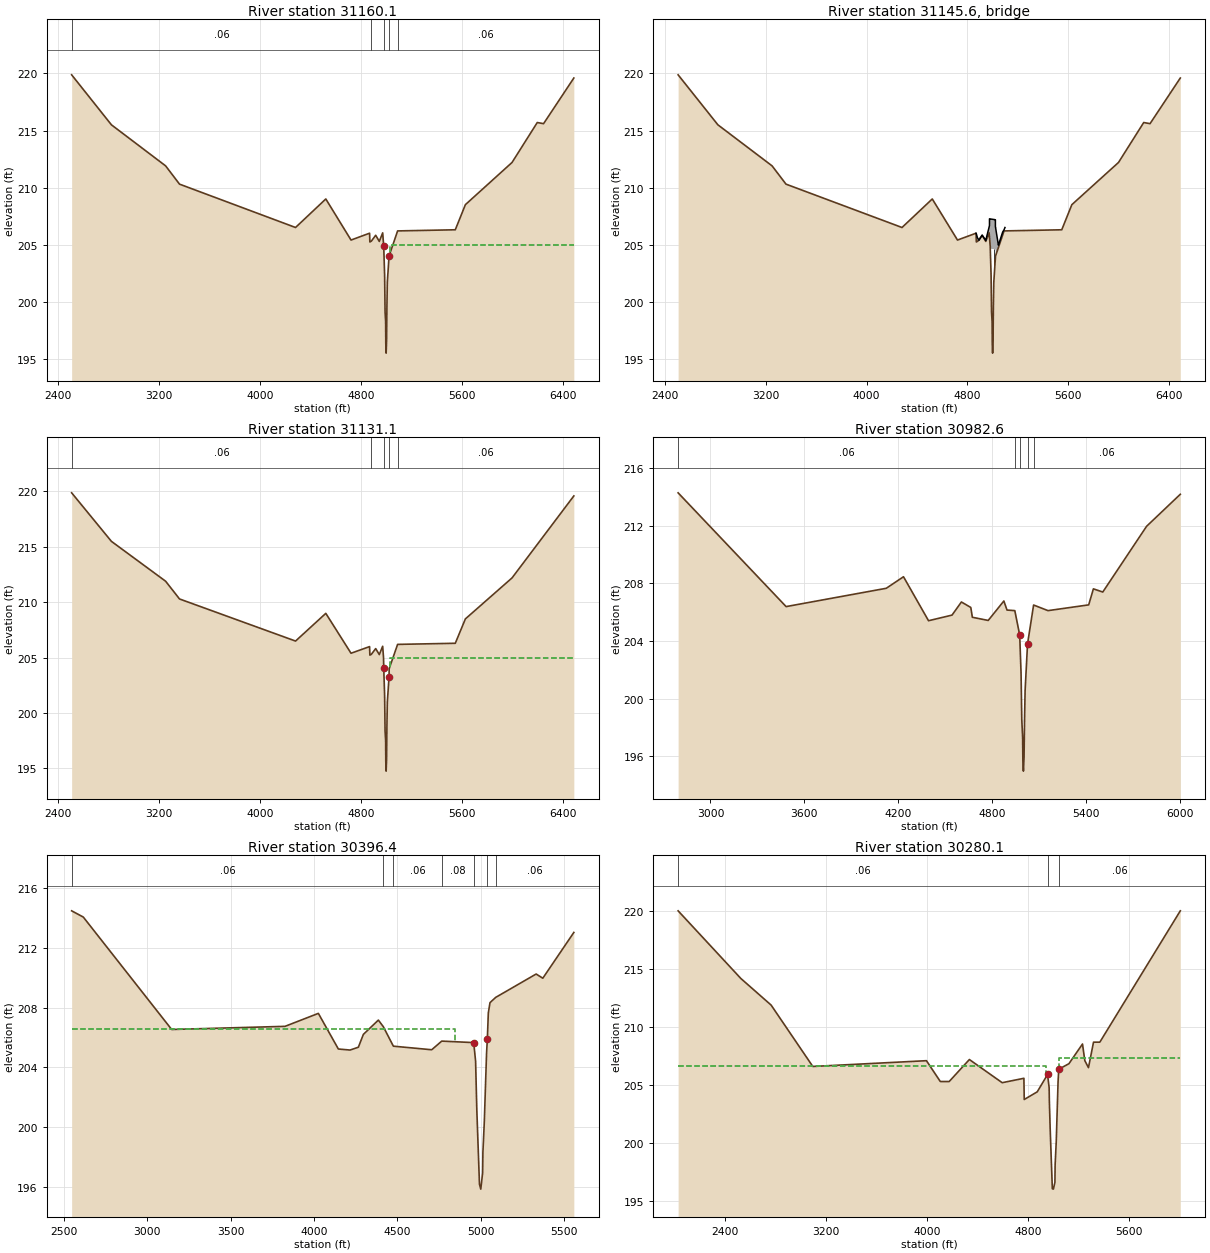
Type RM Length L Ch R = 1 ,31160.1 ,30,29,28
BEGIN DESCRIPTION:
S1a_PRIVATE ROAD - XS3
END DESCRIPTION:
XS GIS Cut Line= 5
 2948077.080713213928917.1679746      2947176.42     13926733.22
      2946953.44     13926786.93      2946809.27     13926829.46
 2945689.404330213926297.1167022
#Sta/Elev= 30
  2505.7  219.88    2821   215.5    3251   211.9    3361   210.3    4281   206.5
    4521     209    4721   205.4  4868.1     206  4870.3  205.23  4881.9   205.3
  4916.5  205.82  4945.2  205.28  4971.9  206.03  4980.3  204.84  4987.4   202.3
    4991  199.07  4995.4  198.24  4996.6  196.36  4999.4  195.49    5003  196.62
  5005.6  199.61  5008.8  201.71  5022.4  203.99  5090.3   206.2  5547.7   206.3
  5627.7   208.5  5997.7   212.2  6197.7   215.7  6247.7   215.6  6487.7   219.6
#Mann= 5 ,-1 , 0
  2505.7     .06       0  4881.9     .08       0  4980.3     .08       0
  5022.4     .08       0  5090.3     .06       0
#XS Ineff= 2 , 0
       0  4970.3  205.37  5032.4       0  204.95
Permanent Ineff=
       F       F
Bank Sta=4980.3,5022.4
Exp/Cntr=0.5,0.3

Type RM Length L Ch R = 3 ,31145.6 ,,,
BEGIN DESCRIPTION:
PRIVATE ROAD 850 FT US MATHIS RD
Structure ID: K166-00-00-S1a
END DESCRIPTION:
Bridge Culvert--1,0,-1,-1, 0
Deck Dist Width WeirC Skew NumUp NumDn MinLoCord MaxHiCord MaxSubmerge Is_Ogee
10,9,2.6,0, 45, 45, , , 0.95, 0, 1,1,,
  4868.1  4869.1  4869.5  4870.3  4879.1  4881.9  4891.6  4892.1    4916  4916.5
    4945  4945.2  4971.9 4974.49  4974.6 4974.71  4975.6  4978.7  4980.3 4980.91
    4981  4987.4    4991  4995.4  4996.2  4996.6  4999.4    5003  5003.9  5005.6
  5008.8  5012.3  5018.8  5021.1 5021.39  5021.5 5021.61  5022.4 5023.29  5023.4
  5044.8  5045.4  5079.1  5090.3  5097.4
     206     206  205.98  205.95   205.6  205.55  205.39  205.38  205.82  205.83
  205.37  205.38  206.55  206.66  207.26  207.26  207.26  207.25  207.25  207.25
  207.25  207.24  207.23  207.22  207.22  207.22  207.22  207.21  207.21  207.21
   207.2   207.2  207.18  207.18  207.18  207.18  206.58  206.53  206.46  206.46
  204.99  204.95   206.1   206.3   206.5
     206  205.56  205.38  205.23  205.29   205.3  205.37  205.37  205.81  205.82
  205.28  205.28  206.03  205.65  205.63  205.61  205.48  205.01  204.84  204.62
  204.65  204.64  204.63  204.62  204.62  204.62  204.62  204.61  204.61  204.61
   204.6   204.6  204.58  204.58  204.58  204.58  204.58  204.53  204.46     204
  204.25  204.28  205.72   206.2   206.5
  4868.1  4869.1  4869.5  4870.3  4879.1  4881.9  4891.6  4892.1    4916  4916.5
    4945  4945.2  4971.9 4974.49  4974.6 4974.71  4975.6  4978.7  4980.3 4980.91
    4981  4987.4    4991  4995.4  4996.2  4996.6  4999.4    5003  5003.9  5005.6
  5008.8  5012.3  5018.8  5021.1 5021.39  5021.5 5021.61  5022.4 5023.29  5023.4
  5044.8  5045.4  5079.1  5090.3  5097.4
     206     206  205.98  205.95   205.6  205.55  205.39  205.38  205.82  205.83
  205.37  205.38  206.55  206.66  207.26  207.26  207.26  207.25  207.25  207.25
  207.25  207.24  207.23  207.22  207.22  207.22  207.22  207.21  207.21  207.21
   207.2   207.2  207.18  207.18  207.18  207.18  206.58  206.53  206.46  206.46
  204.99  204.95   206.1   206.3   206.5
     206  205.56  205.38  205.23  205.29   205.3  205.37  205.37  205.81  205.82
  205.28  205.28  206.03  205.65  205.63  205.61  205.48  204.62  204.62  204.62
  204.65  204.64  204.63  204.62  204.62  204.62  204.62  204.61  204.61  204.61
   204.6   204.6  204.58  204.58  204.58  204.58  204.58  204.53  204.46     204
  204.25  204.28  205.72   206.2   206.5
Pier Skew, UpSta & Num, DnSta & Num=  ,5012.3, 2 ,5012.3, 2 , 0 , 0 , 0 ,,
       1       1
  201.46   205.6
       1       1
  200.72  204.86
BR Coef= 1 , 1 , 1 ,1.25, 0 ,,,0.8,0,2,0,
WSPro=,,,, 1 ,,,, 0 ,,,, 0 ,,,,-1 ,-1 ,-1 , 0 , 0 , 0 , 0 , 0
BR D #Sta/Elev= 82
    2011     227    2031   226.2    2061   226.3    2821   215.5    3251   211.9
    3261   211.5    3341   210.9    3361   210.3    4281   206.5    4421   208.1
    4521     209    4641   206.6    4721   205.4    4821   205.8  4868.1     206
  4869.1  205.56  4869.5  205.38  4870.3  205.23  4879.1  205.29  4881.9   205.3
  4891.6  205.37  4892.1  205.37    4916  205.81  4916.5  205.82    4945  205.28
  4945.2  205.28  4971.9  206.03 4974.49  205.65  4974.6  205.63 4974.71  205.61
  4975.6  205.48  4978.7  205.01  4980.3  204.11 4980.91  203.89    4981  203.86
  4987.4  201.57    4991  198.34  4995.4  197.51  4996.2  196.63  4996.6  195.63
  4999.4  194.76    5003  195.89  5003.9  196.62  5005.6  198.88  5008.8  200.98
  5012.3  201.86  5018.8  202.56  5021.1  203.13 5021.39  203.16  5021.5  203.17
 5021.61  203.18  5022.4  203.26 5023.29     204  5023.4     204  5044.8  204.25
  5045.4  204.28  5079.1  205.72  5090.3   206.2  5097.4   206.5  5247.7     206
  5547.7   206.3  5587.7   207.3  5597.7   207.3  5627.7   208.5  5707.7   208.9
  5877.7   210.8  5987.7   212.3  5997.7   212.2  6027.7   213.1  6047.7   212.9
  6067.7   213.4  6197.7   215.7  6217.7   215.5  6237.7   215.8  6247.7   215.6
  6317.7     217  6327.7   217.5  6357.7   217.8  6397.7     218  6487.7   219.6
  6517.7   220.9  6567.7   221.2
BR D #Mann= 5
    2011     .06  4881.9     .08  4980.3     .08  5022.4     .08  5090.3     .06
BC Design=,, 0 ,, 0 ,,,,,,
BC HTab HWMax=227

Type RM Length L Ch R = 1 ,31131.1 ,149.5,148.5,147.5
BEGIN DESCRIPTION:
S1a_PRIVATE ROAD - XS2
END DESCRIPTION:
XS GIS Cut Line= 5
 2948072.180429313928890.7280917      2947169.89     13926702.83
      2946942.62     13926757.57      2946800.17     13926799.59
 2945682.026690113926268.0717379
#Sta/Elev= 30
  2505.7  219.88    2821   215.5    3251   211.9    3361   210.3    4281   206.5
    4521     209    4721   205.4  4868.1     206  4870.3  205.23  4881.9   205.3
  4916.5  205.82  4945.2  205.28  4971.9  206.03  4978.7  205.01  4980.3  204.11
  4987.4  201.57    4991  198.34  4995.4  197.51  4996.6  195.63  4999.4  194.76
    5003  195.89  5005.6  198.88  5008.8  200.98  5022.4  203.26 5023.29     204
  5090.3   206.2  5547.7   206.3  5627.7   208.5  5997.7   212.2  6487.7   219.6
#Mann= 5 ,-1 , 0
  2505.7     .06       0  4881.9     .08       0  4980.3     .08       0
  5022.4     .08       0  5090.3     .06       0
#XS Ineff= 2 , 0
       0 4973.63  205.37 5029.07       0  204.95
Permanent Ineff=
       F       F
Bank Sta=4980.3,5022.4
Exp/Cntr=0.5,0.3

Type RM Length L Ch R = 1 ,30982.6 ,40,586.2,636
BEGIN DESCRIPTION:
S1a_PRIVATE ROAD - XS1
END DESCRIPTION:
XS GIS Cut Line= 4
      2947884.55     13928351.77      2947128.84     13926520.21
      2946799.14     13926713.11       2946035.7      13926350.2
#Sta/Elev= 30
  2793.4  214.28  3483.4  206.39  4123.4  207.66  4233.4  208.46  4393.4  205.41
  4543.4   205.8  4603.4  206.71  4663.4  206.33  4673.4  205.65  4774.7  205.43
  4874.7  206.78  4894.7  206.15  4944.7  206.11 4975.81  204.42 4984.66  201.73
 4989.14  198.55 4994.62  197.32 4996.12  195.71 4999.61  194.98 5003.73  195.94
 5006.72  198.46 5010.39  200.57 5025.98   203.8  5064.7   206.5  5156.7  206.11
  5416.7  206.51  5446.7  207.62  5506.7   207.4  5786.7  211.96    6002  214.18
#Mann= 5 ,-1 , 0
  2793.4     .06       0  4944.7     .08       0 4975.81     .08       0
 5025.98     .08       0  5064.7     .06       0
Bank Sta=4975.81,5025.98
Exp/Cntr=0.3,0.1

Type RM Length L Ch R = 1 ,30396.4 ,18,116.3,185
BEGIN DESCRIPTION:
S1_Mathis - XS4
END DESCRIPTION:
XS GIS Cut Line= 4
      2947894.28     13928335.78      2947002.03     13926118.97
      2946896.47      13926048.6      2946466.58     13925801.04
#Sta/Elev= 30
  2546.2   214.5  2616.2  214.08  3146.2  206.54  3826.2  206.75  4026.2  207.62
  4146.2  205.23  4216.2  205.16  4266.2  205.35  4296.2  206.21  4386.2  207.17
  4416.2  206.72  4476.2  205.42  4706.2  205.18  4766.2  205.76 4958.11  205.66
 4969.43  204.42 4976.79  201.15 4992.71  196.16 5000.44  195.83 5011.69  196.92
 5013.28   198.3 5021.63  200.32 5035.13  204.92  5040.1  205.93  5045.8  207.65
  5055.8  208.34    5090 208.693  5332.7  210.26  5372.7  209.98  5558.8  213.05
#Mann= 7 ,-1 , 0
  2546.2     .06       0  4416.2     .08       0  4476.2     .06       0
  4766.2     .08       0 4958.11     .08       0  5040.1     .08       0
    5090     .06       0
#XS Ineff= 2 , 0
       0    4845   206.6               0
Permanent Ineff=
       F       F
Bank Sta=4958.11,5040.1
Exp/Cntr=0.5,0.3

Type RM Length L Ch R = 1 ,30280.1 ,59,60,61
BEGIN DESCRIPTION:
S1_Mathis - XS3
END DESCRIPTION:
XS GIS Cut Line= 4
 2948079.7341747 13928763.123448      2947076.78     13926244.38
      2946941.74     13925743.41 2946213.6612405 13925575.005148
#Sta/Elev= 30
 2028.49  220.03  2525.2  214.19  2765.2  211.89  3095.2  206.59  3995.2  207.09
  4105.2  205.29  4175.2  205.29  4335.2  207.19  4595.2  205.19    4767  205.57
  4769.7  203.74  4872.6   204.4  4954.6   205.9  4966.9  204.76  4968.5  203.65
  4974.9  201.27  4992.2  196.04  5000.6     196  5012.6  196.58  5014.3  198.08
  5023.2   200.1  5037.6  205.27  5042.9  206.35  5123.6  206.83  5231.1  208.53
  5249.6  207.09  5278.4  206.49  5318.4  208.69  5368.4  208.69  6005.7  220.03
#Mann= 3 ,-1 , 0
 2028.49     .06       0  4954.6     .08       0  5042.9     .06       0
#XS Ineff= 2 , 0
       0    4945   206.6    5048       0   207.3
Permanent Ineff=
       F       F
Bank Sta=4954.6,5042.9
Exp/Cntr=0.5,0.3