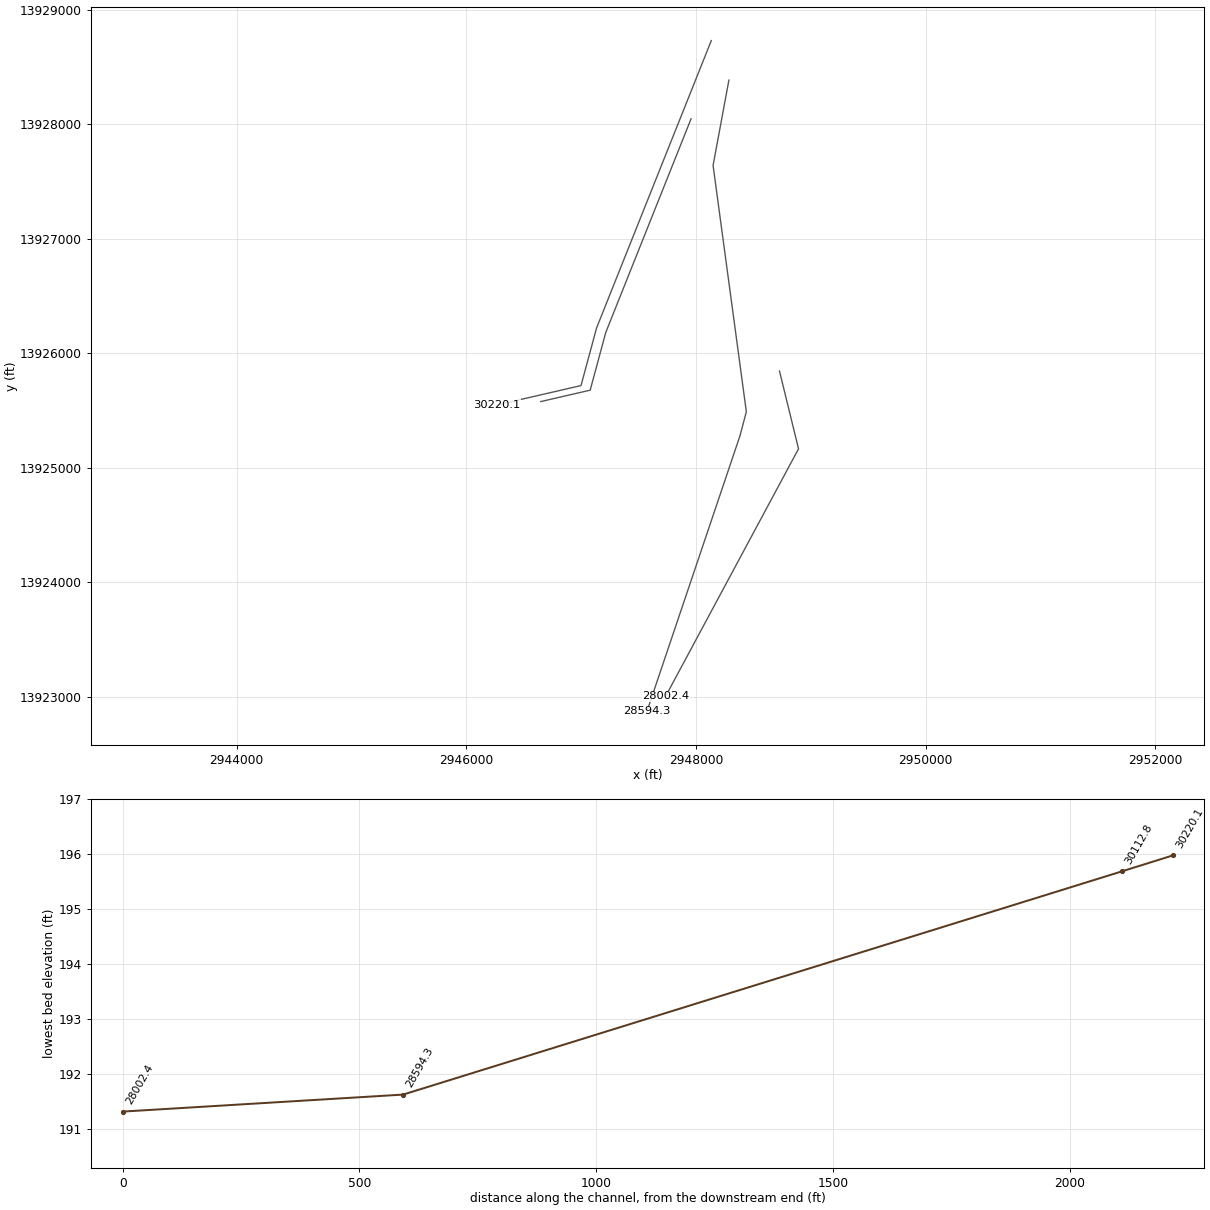
HEC-RAS study K166-00-00.prj: K166-00-00

--- K166-00-00.g01 (geometry) --- (continued)

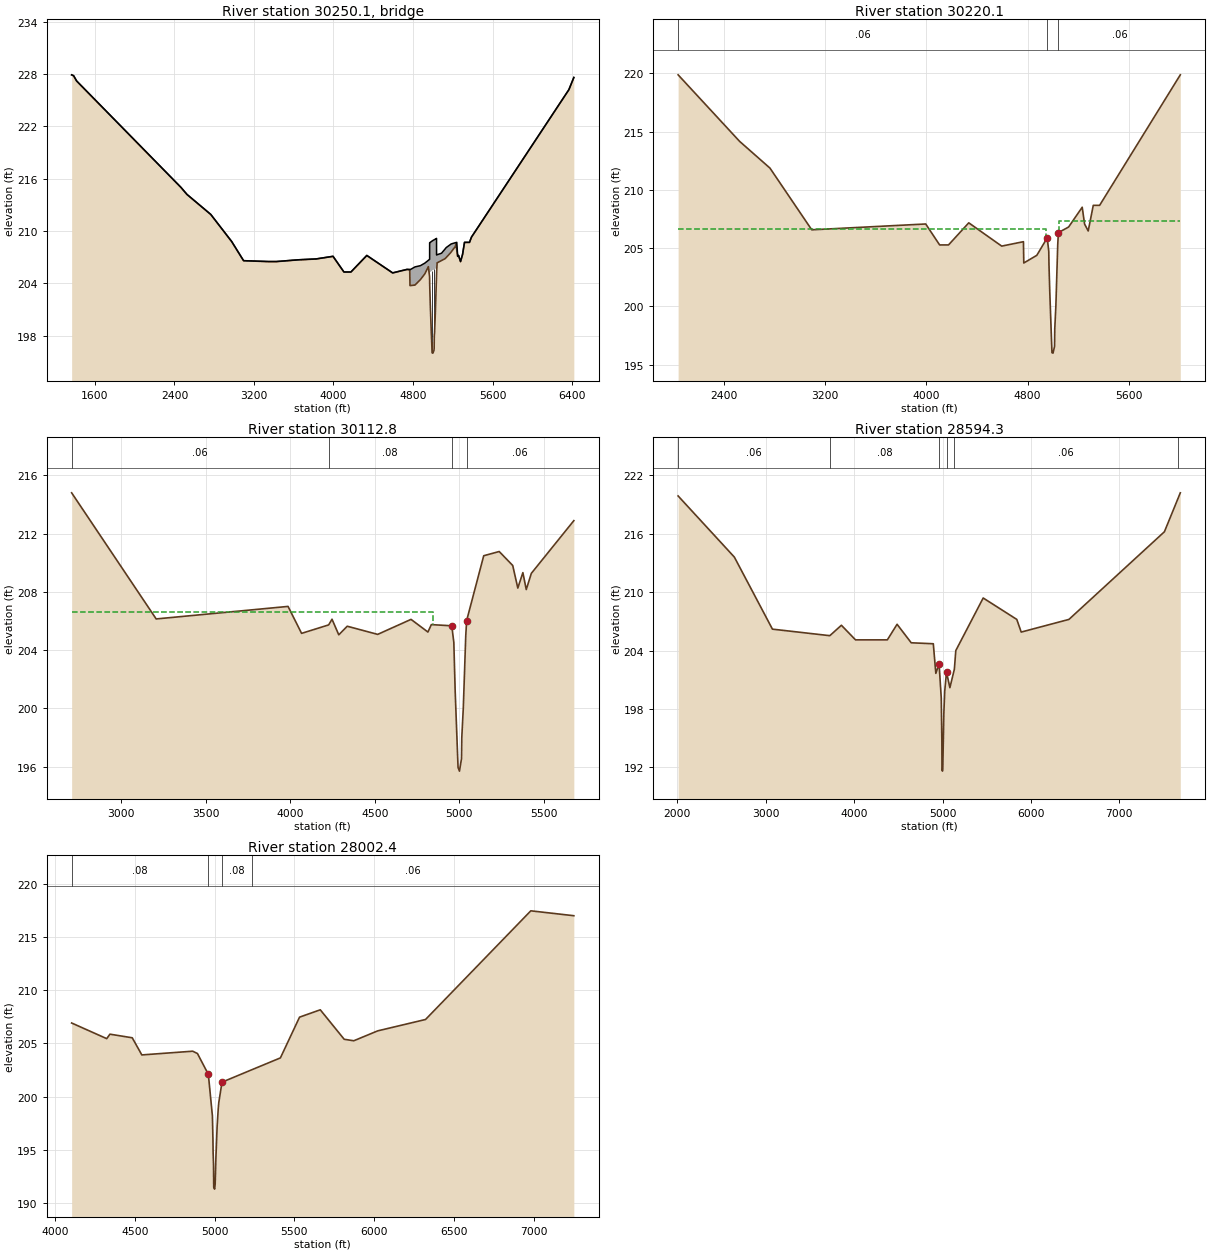
Type RM Length L Ch R = 3 ,30250.1 ,,,
BEGIN DESCRIPTION:
MATHIS
Structure ID: K166-00-00-S1
END DESCRIPTION:
Bridge Culvert--1,0,-1,-1, 0
Deck Dist Width WeirC Skew NumUp NumDn MinLoCord MaxHiCord MaxSubmerge Is_Ogee
10,40,2.6,0, 73, 73, , , 0.95, 0, 1,1,,
  1365.2  1385.2  1415.2  2465.2  2525.2  2765.2  2975.2  3095.2  3345.2  3425.2
  3645.2  3825.2  3995.2  4105.2  4175.2  4335.2  4595.2  4739.6  4761.1    4767
  4769.7  4819.6  4821.6  4872.6  4874.9  4917.9  4919.2  4954.6  4966.9    4967
 4967.11 4967.21 4967.32 4967.43  4967.5  4968.5  4974.9    4985  4985.7  4992.2
  5000.6  5001.1  5010.9  5012.6  5014.3  5016.8  5023.2  5034.3 5036.89    5037
 5037.11  5037.6 5037.79  5037.9    5038  5042.9  5086.7  5123.6  5134.2  5175.1
  5183.1  5227.1  5231.1  5240.7  5249.6  5258.4  5278.4  5298.4  5318.4  5368.4
  5388.4  6368.4  6418.4
   227.9   227.8   227.2     215   214.2   211.9   208.8   206.6   206.5   206.5
   206.7   206.8   207.1   205.3   205.3   207.2   205.2   205.6  205.59  205.59
  205.56  205.88  205.89  206.02  206.03  206.31  206.32  206.64  206.75  206.75
  206.75  206.75  208.65  208.65  208.65  208.66  208.71  208.79   208.8  208.85
  208.92  208.92  208.98  208.99     209  209.02  209.06  209.13  209.15  209.15
  207.25  207.26  207.26  207.26  207.26  207.28  207.45  207.95   208.1  208.44
  208.51  208.66  208.67   208.7   207.1   207.2   206.5   207.3   208.7   208.7
   209.3   226.2   227.6
                                                                                
                                                                                
                                                          205.91  204.77   204.7
  204.62  204.55  204.48   204.4  205.25  205.26  205.31  205.39   205.4  205.45
  205.52  205.52  205.58  205.59   205.6  205.62  205.66  205.73  205.75  205.75
  205.75  205.76  205.76  205.34  205.36  206.36
                                                                                
                        
  1365.2  1385.2  1415.2  2465.2  2525.2  2765.2  2975.2  3095.2  3345.2  3425.2
  3645.2  3825.2  3995.2  4105.2  4175.2  4335.2  4595.2  4739.6  4761.1    4767
  4769.7  4819.6  4821.6  4872.6  4874.9  4917.9  4919.2  4954.6  4966.9    4967
 4967.11 4967.21 4967.32 4967.43  4967.5  4968.5  4974.9    4985  4985.7  4992.2
  5000.6  5001.1  5010.9  5012.6  5014.3  5016.8  5023.2  5034.3 5036.89    5037
 5037.11  5037.6 5037.79  5037.9    5038  5042.9  5086.7  5123.6  5134.2  5175.1
  5183.1  5227.1  5231.1  5240.7  5249.6  5258.4  5278.4  5298.4  5318.4  5368.4
  5388.4  6368.4  6418.4
   227.9   227.8   227.2     215   214.2   211.9   208.8   206.6   206.5   206.5
   206.7   206.8   207.1   205.3   205.3   207.2   205.2   205.6  205.59  205.59
  205.56  205.88  205.89  206.02  206.03  206.31  206.32  206.64  206.75  206.75
  206.75  206.75  208.65  208.65  208.65  208.66  208.71  208.79   208.8  208.85
  208.92  208.92  208.98  208.99     209  209.02  209.06  209.13  209.15  209.15
  207.25  207.26  207.26  207.26  207.26  207.28  207.45  207.95   208.1  208.44
  208.51  208.66  208.67   208.7   207.1   207.2   206.5   207.3   208.7   208.7
   209.3   226.2   227.6
                                                                                
                                                                                
                                                          205.91  204.77   204.7
  204.62  204.55  204.48   204.4  205.25  205.26  205.31  205.39   205.4  205.45
  205.52  205.52  205.58  205.59   205.6  205.62  205.66  205.73  205.75  205.75
  205.75  205.76  205.76  205.34  205.36  206.36
                                                                                
                        
Pier Skew, UpSta & Num, DnSta & Num=  ,4992.6, 2 ,4992.6, 2 , 0 , 0 , 0 ,,
     1.4     1.4
  195.04  206.46
     1.4     1.4
  195.04  206.46
Pier Skew, UpSta & Num, DnSta & Num=  ,5012.6, 2 ,5012.6, 2 , 0 , 0 , 0 ,,
     1.4     1.4
  195.48  206.59
     1.4     1.4
  195.48  206.59
BR Coef= 1 , 1 , 1 ,1.25, 0 ,,,0.8,0,2,0,
WSPro=,,,, 1 ,,,, 0 ,,,, 0 ,,,,-1 ,-1 ,-1 , 0 , 0 , 0 , 0 , 0
BR U #Sta/Elev= 73
  1365.2  227.89  1385.2  227.79  1415.2  227.19  2465.2  214.99  2525.2  214.19
  2765.2  211.89  2975.2  208.79  3095.2  206.59  3345.2  206.49  3425.2  206.49
  3645.2  206.69  3825.2  206.79  3995.2  207.09  4105.2  205.29  4175.2  205.29
  4335.2  207.19  4595.2  205.19  4739.6  205.59  4761.1  205.57    4767  205.57
  4769.7  203.74  4819.6   203.8  4821.6  203.82  4872.6   204.4  4874.9  204.43
  4917.9  205.07  4919.2  205.09  4954.6  205.91  4966.9  204.76    4967  204.69
 4967.11  204.61 4967.21  204.54 4967.32  204.47 4967.43  204.39  4967.5  204.34
  4968.5  203.65  4974.9  201.27    4985   198.1  4985.7  198.01  4992.2  196.04
  5000.6     196  5001.1  196.02  5010.9  196.31  5012.6  196.58  5014.3  198.08
  5016.8   198.3  5023.2   200.1  5034.3  204.02 5036.89     205    5037  205.04
 5037.11  205.08  5037.6  205.27 5037.79  205.31  5037.9  205.33    5038  205.35
  5042.9  206.35  5086.7  206.61  5123.6  206.83  5134.2  206.96  5175.1  207.46
  5183.1  207.58  5227.1  208.24  5231.1  208.53  5240.7  207.78  5249.6  207.09
  5258.4  207.19  5278.4  206.49  5298.4  207.29  5318.4  208.69  5368.4  208.69
  5388.4  209.29  6368.4  226.19  6418.4  227.59
BR U #Mann= 3
  1365.2     .06  4954.6     .08  5042.9     .06
BR D #Sta/Elev= 73
  1365.2  227.87  1385.2  227.77  1415.2  227.17  2465.2  214.97  2525.2  214.17
  2765.2  211.87  2975.2  208.77  3095.2  206.57  3345.2  206.47  3425.2  206.47
  3645.2  206.67  3825.2  206.77  3995.2  207.07  4105.2  205.27  4175.2  205.27
  4335.2  207.17  4595.2  205.17  4739.6  205.57  4761.1  205.55    4767  205.55
  4769.7  203.72  4819.6  203.78  4821.6   203.8  4872.6  204.38  4874.9  204.41
  4917.9  205.05  4919.2  205.07  4954.6  205.88  4966.9  204.74    4967  204.67
 4967.11  204.59 4967.21  204.52 4967.32  204.45 4967.43  204.37  4967.5  204.32
  4968.5  203.63  4974.9  201.25    4985  198.08  4985.7  197.99  4992.2  196.02
  5000.6  195.98  5001.1     196  5010.9  196.29  5012.6  196.56  5014.3  198.06
  5016.8  198.28  5023.2  200.08  5034.3     204 5036.89  204.98    5037  205.02
 5037.11  205.06  5037.6  205.25 5037.79  205.29  5037.9  205.31    5038  205.33
  5042.9  206.33  5086.7  206.59  5123.6  206.81  5134.2  206.94  5175.1  207.44
  5183.1  207.56  5227.1  208.22  5231.1  208.51  5240.7  207.76  5249.6  207.07
  5258.4  207.17  5278.4  206.47  5298.4  207.27  5318.4  208.67  5368.4  208.67
  5388.4  209.27  6368.4  226.17  6418.4  227.57
BR D #Mann= 3
  1365.2     .06  4954.6     .08  5042.9     .06
BC Design=,, 0 ,, 0 ,,,,,,
BC HTab HWMax=227.89

Type RM Length L Ch R = 1 ,30220.1 ,106.3,107.3,108.3
BEGIN DESCRIPTION:
S1_Mathis - XS2
END DESCRIPTION:
XS GIS Cut Line= 4
 2948133.458624113928729.5114844      2947134.83     13926221.62
      2946999.08     13925718.04 2946268.080590113925548.9579599
#Sta/Elev= 30
 2039.89  219.88  2525.2  214.17  2765.2  211.87  3095.2  206.57  3995.2  207.07
  4105.2  205.27  4175.2  205.27  4335.2  207.17  4595.2  205.17    4767  205.55
  4769.7  203.72  4872.6  204.38  4954.6  205.88  4966.9  204.74  4968.5  203.63
  4974.9  201.25  4992.2  196.02  5000.6  195.98  5012.6  196.56  5014.3  198.06
  5023.2  200.08  5037.6  205.25  5042.9  206.33  5123.6  206.81  5231.1  208.51
  5249.6  207.07  5278.4  206.47  5318.4  208.67  5368.4  208.67  6005.7  219.88
#Mann= 3 ,-1 , 0
 2039.89     .06       0  4954.6     .08       0  5042.9     .06       0
#XS Ineff= 2 , 0
       0    4945   206.6    5048       0   207.3
Permanent Ineff=
       F       F
Bank Sta=4954.6,5042.9
Exp/Cntr=0.5,0.3

Type RM Length L Ch R = 1 ,30112.8 ,1190,1518.5,1423
BEGIN DESCRIPTION:
S1_Mathis - XS1
END DESCRIPTION:
XS GIS Cut Line= 4
      2947957.14     13928046.38      2947214.54     13926181.46
      2947078.79     13925677.88      2946648.69      13925578.4
#Sta/Elev= 30
  2706.7   214.8  3206.7  206.14  3986.7     207  4066.7  205.15  4226.7  205.73
  4246.7  206.12  4286.7  205.05  4336.7  205.64  4516.7  205.08    4714  206.11
    4814  205.24    4834  205.75 4955.03  205.67 4967.19  204.53  4975.1   201.2
  4992.2  195.94 5000.51  195.69 5012.57  196.55 5014.28     198 5023.23  200.04
 5037.71  204.98 5043.04  206.03    5144  210.48  5235.6  210.77  5315.6  209.81
  5345.6  208.26  5375.6  209.32  5395.6  208.16  5425.6  209.27    5677  212.89
#Mann= 4 ,-1 , 0
  2706.7     .06       0  4226.7     .08       0 4955.03     .08       0
 5043.04     .06       0
#XS Ineff= 2 , 0
       0    4845   206.6               0
Permanent Ineff=
       F       F
Bank Sta=4955.03,5043.04
Exp/Cntr=0.3,0.1

Type RM Length L Ch R = 1 ,28594.3 ,671,592.3,517.8
BEGIN DESCRIPTION:
Cross Section K166-00-00-X28
Overbank Reach lengths changed by JJA on 3/12/03
END DESCRIPTION:
XS GIS Cut Line= 5
  2948286.65296113928384.1193573      2948148.92     13927639.49
      2948438.53     13925489.75      2948383.76     13925281.62
 2947573.237841313922874.3864902
#Sta/Elev= 30
 2008.55  219.88    2645   213.6  3075.8   206.2  3724.8  205.53  3855.8   206.6
  4015.8   205.1  4375.8   205.1  4485.8   206.7  4645.8   204.8  4895.8   204.7
  4924.2  201.66  4961.1  202.63  4985.8  199.12  4992.6  194.61  4993.9  191.81
  4999.2  191.62  5002.7  191.83  5015.1   197.6    5025  199.84    5045  201.79
  5083.3  200.19    5134  202.09  5150.2     204  5460.2   209.4  5840.2   207.2
  5890.2   205.9  6430.2   207.2  7510.2   216.2    7662  219.57  7690.2   220.2
#Mann= 6 ,-1 , 0
 2008.55     .06       0  3724.8     .08       0  4961.1     .07       0
    5045     .08       0    5134     .06       0    7662     .04       0
#XS Ineff= 2 , 0
                          5460.2           209.4
Permanent Ineff=
       F       F
Bank Sta=4961.1,5045
Exp/Cntr=0.3,0.1

Type RM Length L Ch R = 1 ,28002.4 ,888.7,1418.1,410.5
BEGIN DESCRIPTION:
Cross Section K166-00-00-interpolatedxs -1
END DESCRIPTION:
XS GIS Cut Line= 3
      2948727.13      13925844.8      2948892.84      13925165.8
      2947736.15     13923006.36
#Sta/Elev= 30
  4103.8  206.92  4323.8  205.45  4343.8  205.87  4483.8  205.53  4543.8  203.92
  4862.7  204.27  4892.7  204.05 4960.92  202.09 4986.35  198.19 4989.66  196.02
 4990.78  194.77 4993.35  193.61 4994.69  191.49 5000.14  191.31 5003.69  191.79
 5008.45  194.32 5015.77  197.15 5022.66  198.81 5026.27  199.44 5046.53  201.36
  5232.3  202.52  5412.7  203.64  5532.7  207.47  5662.7  208.16  5812.7  205.39
  5872.7  205.25  6022.7  206.18  6322.7  207.25  6982.7  217.46  7252.5     217
#Mann= 4 ,-1 , 0
  4103.8     .08       0 4960.92     .07       0 5046.53     .08       0
  5232.3     .06       0
Bank Sta=4960.92,5046.53
Exp/Cntr=0.3,0.1