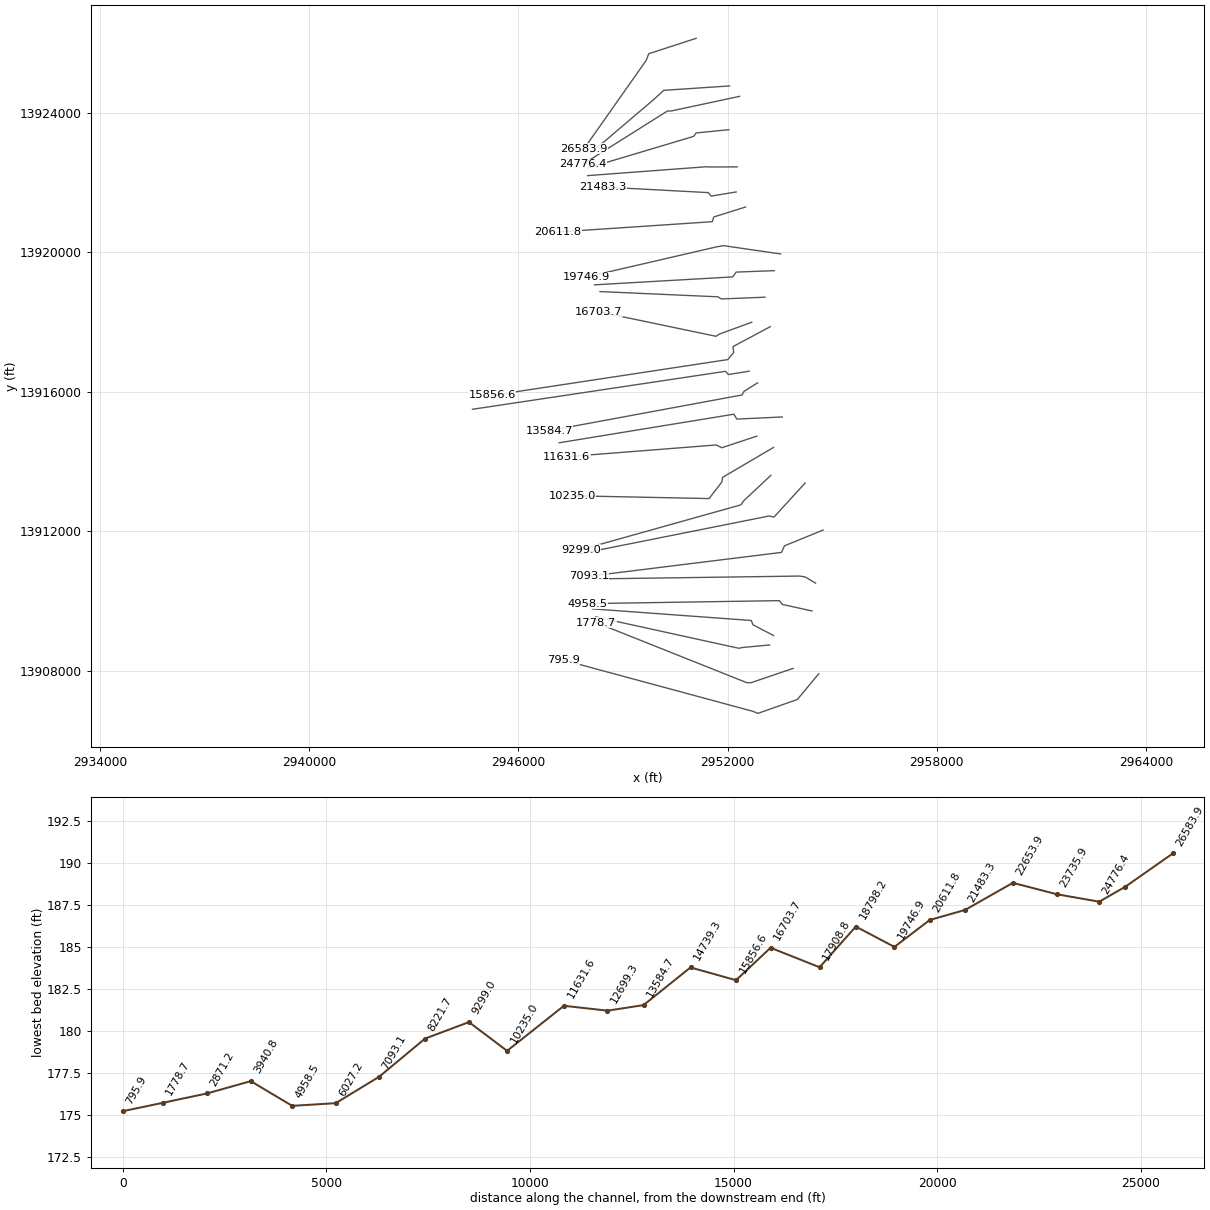
HEC-RAS study K166-00-00.prj: K166-00-00

--- K166-00-00.g01 (geometry) --- (continued)

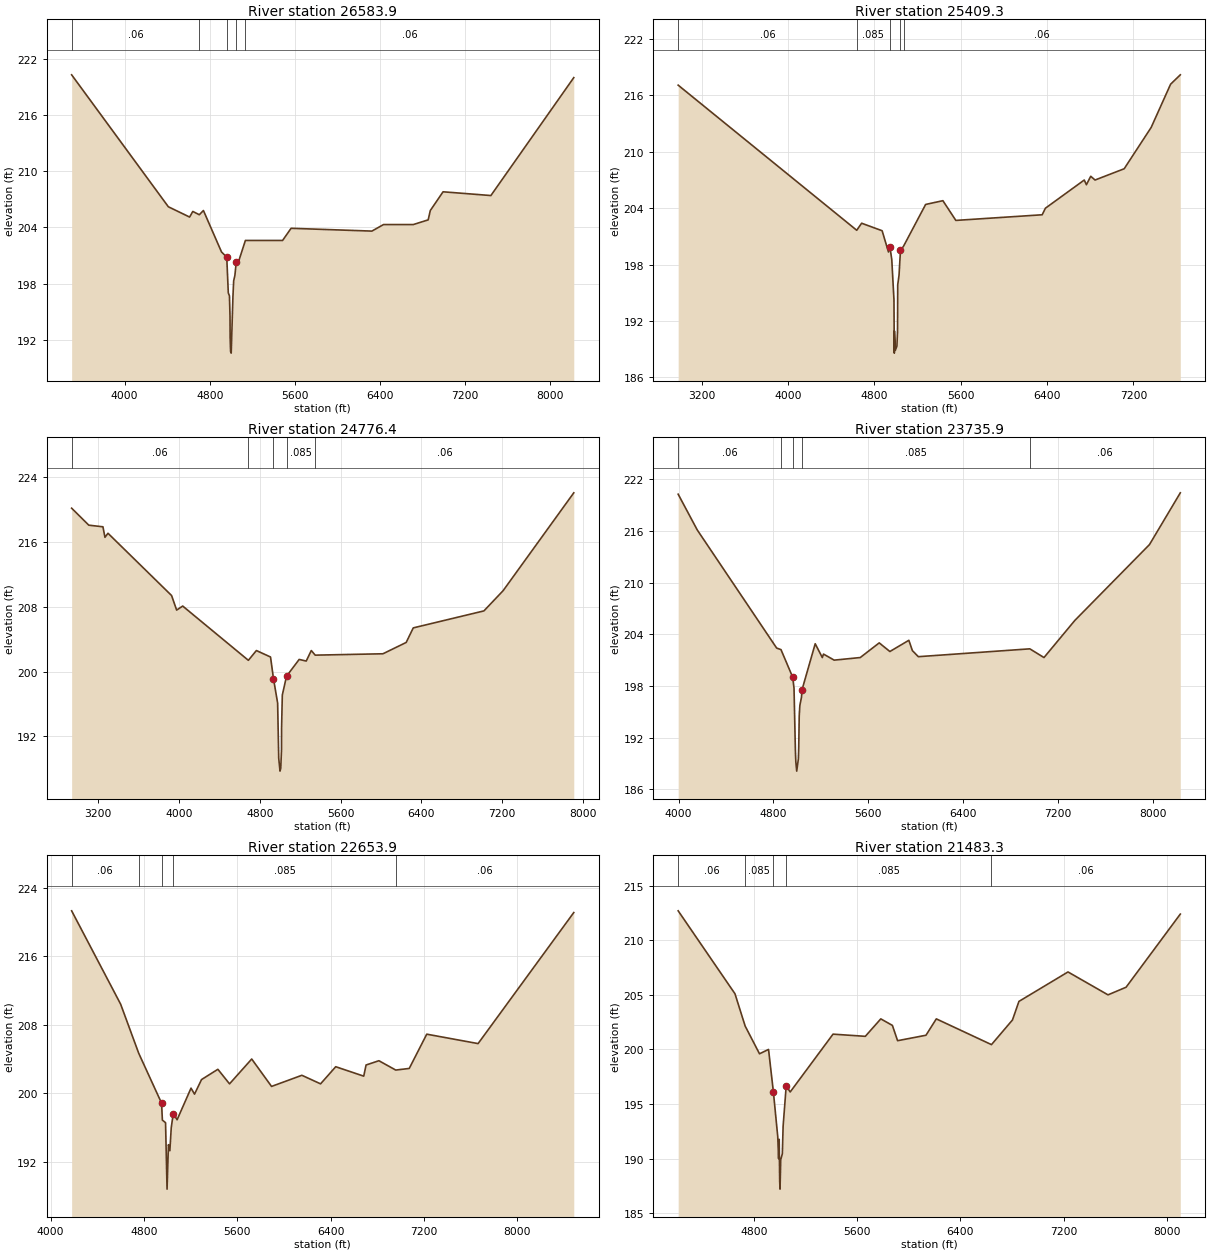
Type RM Length L Ch R = 1 ,26583.9 ,1290.53,1174.6,709.73
BEGIN DESCRIPTION:
Cross Section K166-00-00-X27
END DESCRIPTION:
XS GIS Cut Line= 4
 2951098.910853913926129.5535012      2949738.96     13925688.27
      2949665.73     13925496.63 2947885.835915613922970.7927517
#Sta/Elev= 30
    3501   220.3    4411   206.2    4611   205.1    4641   205.7  4702.3  205.35
    4741   205.8  4910.8  201.38  4960.5  200.81  4975.1  196.99    4986  196.68
  4991.2  194.45  4992.4  192.19  4996.5  190.73  5002.4  190.56  5018.5  196.54
  5025.6  198.28  5037.3  198.88  5050.2  200.34  5063.7  200.07  5135.9   202.6
  5485.9   202.6  5565.9   203.9  6325.9   203.6  6435.9   204.3  6715.9   204.3
  6855.9   204.8  6875.9   205.8  6995.9   207.8  7445.9   207.4  8225.9     220
#Mann= 5 ,-1 , 0
    3501     .06       0  4702.3     .08       0  4960.5     .08       0
  5050.2     .08       0  5135.9     .06       0
#XS Ineff= 2 , 0
                          6995.9           207.8
Permanent Ineff=
       F       F
Bank Sta=4960.5,5050.2
Exp/Cntr=0.3,0.1

Type RM Length L Ch R = 1 ,25409.3 ,622.95,632.9,421.25
BEGIN DESCRIPTION:
Cross Section K166-00-00-X26
Right bank station moved from 5065.8 to 5041.7 by JJA on 3/12/02
END DESCRIPTION:
XS GIS Cut Line= 4
  2952056.18127213924765.2695252      2950170.33     13924639.41
      2949872.43     13924367.86 2948074.196243113922839.5812729
#Sta/Elev= 30
  2981.7   217.1  4636.4  201.65  4681.7   202.4  4871.7   201.6  4930.4  199.34
  4944.5  199.83  4961.1  198.53  4981.3  194.26  4984.5  188.57  4985.6  190.93
  4993.6  188.86  5008.5   189.3  5014.4  190.86  5016.2  195.84  5028.3  196.86
  5041.7  199.51  5069.9  199.95  5274.8   204.4  5434.8   204.8  5554.8   202.7
  6354.8   203.3  6384.8     204  6744.8     207  6764.8   206.5  6804.8   207.4
  6844.8     207  7114.8   208.2  7364.8   212.6  7544.8   217.2  7634.8   218.2
#Mann= 5 ,-1 , 0
  2981.7     .06       0  4636.4    .085       0  4944.5     .08       0
  5041.7    .085       0  5069.9     .06       0
Bank Sta=4944.5,5041.7
Exp/Cntr=0.3,0.1

Type RM Length L Ch R = 1 ,24776.4 ,844.68,1040.5,747.8
BEGIN DESCRIPTION:
Cross Section K166-00-00-X25
END DESCRIPTION:
XS GIS Cut Line= 4
 2952345.8454083 13924467.450575      2950375.92      13924045.8
      2950276.87     13924047.55 2947855.600031613922525.4474918
#Sta/Elev= 30
  2936.6   220.2  3106.6   218.1  3246.6   217.9  3266.6   216.6  3296.6   217.1
  3926.6   209.4  3976.6   207.6  4036.6   208.1  4687.1  201.39  4766.6   202.6
  4906.6   201.8  4935.7  199.13  4976.9  196.11  4987.7  189.29  5000.3  187.69
  5007.9  188.04  5015.2  190.33  5015.9  193.02  5023.3   197.1  5065.1  199.43
  5190.2   201.5  5260.2   201.3  5310.2   202.6    5349  202.03  6020.2   202.2
  6250.2   203.6  6320.2   205.4  7020.2   207.5  7210.2     210  7910.2   222.1
#Mann= 5 ,-1 , 0
  2936.6     .06       0  4687.1    .085       0  4935.7     .08       0
  5065.1    .085       0    5349     .06       0
Bank Sta=4935.7,5065.1
Exp/Cntr=0.3,0.1

Type RM Length L Ch R = 1 ,23735.9 ,1089.12,1082,727.11
BEGIN DESCRIPTION:
Cross Section K166-00-00-X24
END DESCRIPTION:
XS GIS Cut Line= 4
  2952038.07218713923511.5031496      2951097.13     13923417.44
      2951027.11     13923319.42 2947989.628827113922412.7558391
#Sta/Elev= 30
 3997.15  220.24  4157.9   216.1  4827.9   202.4  4864.5  202.22  4963.5  199.01
  4974.4  197.75  4985.9  190.58  4989.6  189.23  4997.2  188.13  5011.2  189.56
  5014.1  190.79  5018.3  194.54  5023.8  195.75  5037.2  196.69  5041.9  197.56
  5153.2   202.9  5213.2   201.3  5223.2   201.7  5313.2     201  5533.2   201.3
  5693.2     203  5783.2     202  5943.2   203.3  5973.2   202.1  6023.2   201.4
  6963.6  202.31  7083.2   201.3  7343.2   205.6  7973.2   214.4  8233.2   220.4
#Mann= 5 ,-1 , 0
 3997.15     .06       0  4864.5    .085       0  4963.5     .08       0
  5041.9    .085       0  6963.6     .06       0
Bank Sta=4963.5,5041.9
Exp/Cntr=0.3,0.1

Type RM Length L Ch R = 1 ,22653.9 ,855.92,1170.6,655.01
BEGIN DESCRIPTION:
Cross Section K166-00-00-X22
END DESCRIPTION:
XS GIS Cut Line= 4
 2952278.313745113922445.2427814       2951517.5     13922442.19
      2951385.39      13922448.8 2947984.893917813922194.7639111
#Sta/Elev= 30
  4181.2   221.3  4601.2   210.4  4755.5  204.69    4952  198.84  4958.7  196.87
  4985.9  196.57  4998.8  188.81  5010.8     194  5022.8  193.29  5034.8     196
    5052  197.63    5085  196.91  5204.3   200.6  5234.3   199.9  5294.3   201.6
  5434.3   202.8  5534.3   201.1  5724.3     204  5894.3   200.8  6154.3   202.1
  6314.3   201.1  6444.3   203.1  6684.3     202  6704.3   203.3  6814.3   203.8
  6958.7  202.71  7074.3   202.9  7224.3   206.9  7664.3   205.8  8484.3   221.1
#Mann= 5 ,-1 , 0
  4181.2     .06       0  4755.5    .085       0    4952     .08       0
    5052    .085       0  6958.7     .06       0
Bank Sta=4952,5052
Exp/Cntr=0.3,0.1

Type RM Length L Ch R = 1 ,21483.3 ,584.61,871.5,978.71
BEGIN DESCRIPTION:
Cross Section K166-00-00-X21
END DESCRIPTION:
XS GIS Cut Line= 4
 2952248.093682613921726.7807489      2951529.06     13921608.26
      2951444.92     13921708.31 2948419.127022713921869.0611008
#Sta/Elev= 30
  4215.1   212.7  4655.1   205.1    4734  202.14  4845.1   199.6  4915.1     200
  4952.7   196.1  4986.4  192.01    4993  189.99  4997.6  191.76  5001.5  187.88
  5004.1   187.2  5009.5   189.9    5022  190.44  5027.9  192.95    5052  196.68
  5082.7   196.1  5414.6   201.4  5664.6   201.2  5784.6   202.8  5874.6   202.2
  5914.6   200.8  6134.6   201.3  6214.6   202.8  6641.9  200.44  6804.6   202.7
  6854.6   204.4  7234.6   207.1  7544.6     205  7684.6   205.7  8104.6   212.4
#Mann= 5 ,-1 , 0
  4215.1     .06       0    4734    .085       0  4952.7     .08       0
    5052    .085       0  6641.9     .06       0
Bank Sta=4952.7,5052
Exp/Cntr=0.3,0.1

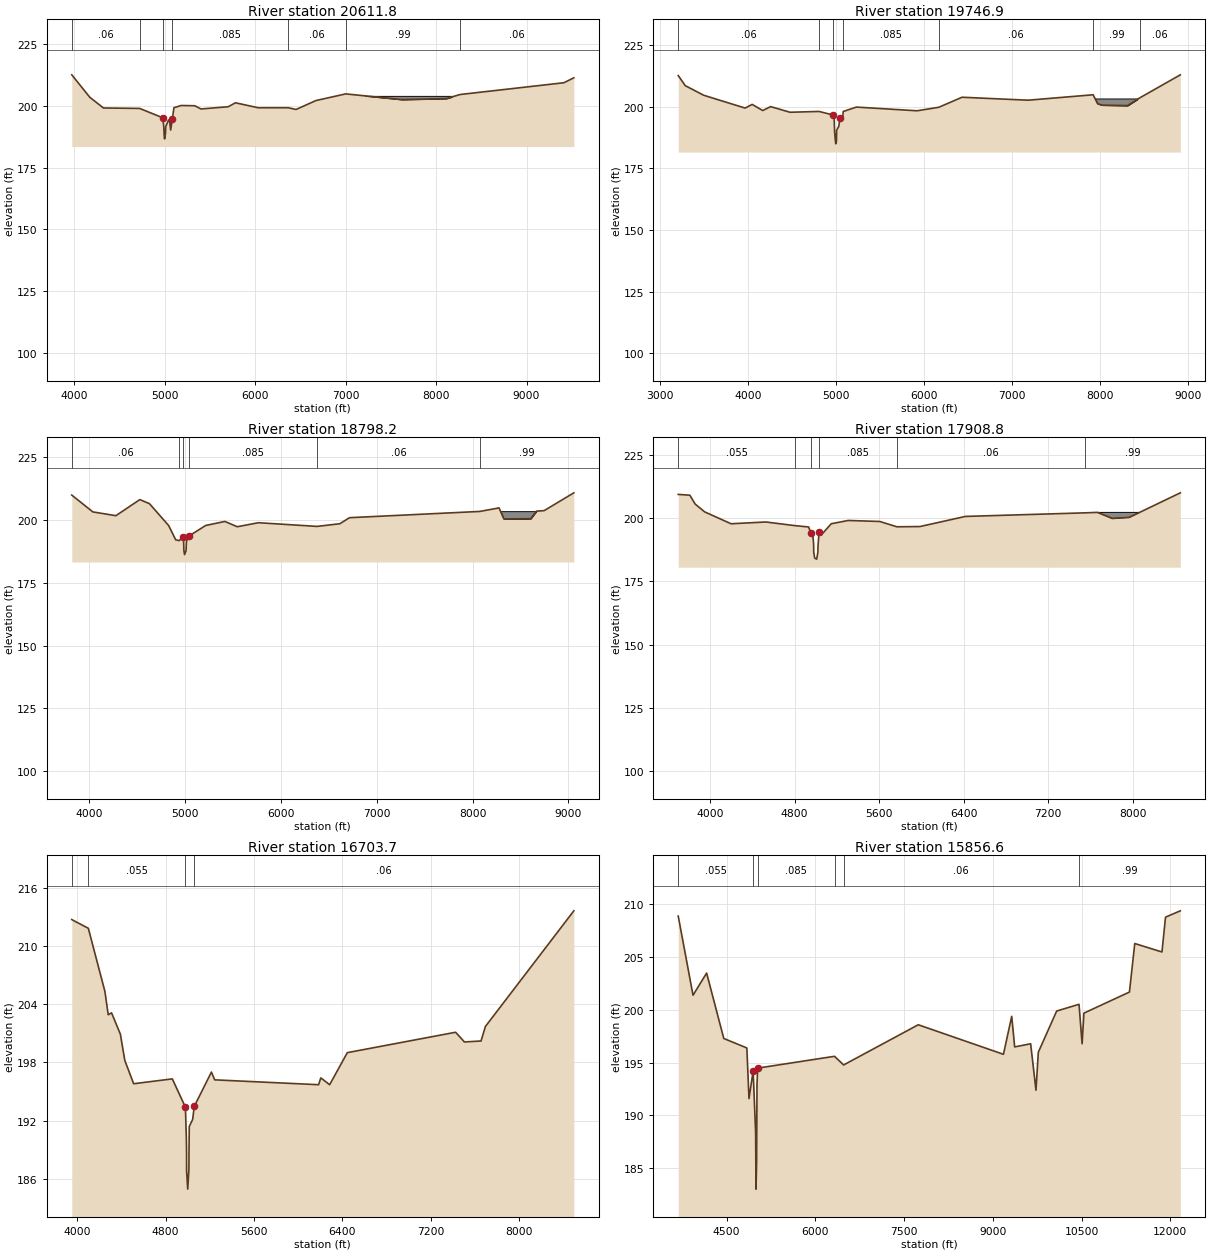
Type RM Length L Ch R = 1 ,20611.8 ,931.01,864.9,840.61
BEGIN DESCRIPTION:
Cross Section K166-00-00-X20
END DESCRIPTION:
XS GIS Cut Line= 4
 2952516.854321913921295.0109569      2951605.98     13921010.79
      2951558.85     13920873.89 2947118.657188113920577.7809013
#Sta/Elev= 30
  3974.2   212.5  4174.2   203.4  4324.2   199.1  4724.3  198.92  4980.1  195.14
  4990.8  191.68  4995.6  188.14  4999.9   186.6  5010.3  188.92  5012.8  191.63
  5043.7  194.25  5057.2  193.39  5067.1  190.19  5085.7  194.63  5103.2   199.2
  5183.2   200.1  5333.2     200  5403.2   198.7  5703.2   199.6  5783.2   201.2
  6033.2   199.2  6365.8   199.2  6453.2   198.5  6673.2   202.1  7002.2  204.79
  7623.2   202.5  8113.2   202.9  8267.2  204.55  9413.2   209.3  9523.2   211.3
#Mann= 7 ,-1 , 0
  3974.2     .06       0  4724.3    .085       0  4980.1     .08       0
  5085.7    .085       0  6365.8     .06       0  7002.2     .99       0
  8267.2     .06       0
#Block Obstruct= 2 ,-1
    7200    8175     204    8500    8510     100
Bank Sta=4980.1,5085.7
Exp/Cntr=0.3,0.1

Type RM Length L Ch R = 1 ,19746.9 ,804.71,948.7,820.23
BEGIN DESCRIPTION:
Cross Section K166-00-00-X19
Right bank station moved from 5080.9 to 5049.9 by JJA on 3/12/03
END DESCRIPTION:
XS GIS Cut Line= 4
 2953523.692482813919949.8777811      2951876.59     13920188.11
      2951670.51     13920149.77  2947938.91007213919287.0158038
#Sta/Elev= 30
  3210.9   212.7  3290.9   208.6  3500.9   204.7  3970.9   199.5  4050.9     201
  4170.9   198.5  4260.9   200.1  4480.9   197.8  4809.7  198.13  4974.2  196.67
  4982.5  194.93  4987.8  189.66  4999.8     185  5008.1   185.9  5010.6  190.51
  5034.8  192.07  5049.9  195.59  5080.9  196.07  5084.8   198.1  5234.8   199.9
  5924.8   198.4  6171.5  199.83  6434.8   203.9  7184.8   202.7  7924.8   204.9
  7974.8   201.3  8024.8   200.7  8314.8   200.5  8451.5  203.59  8914.8     213
#Mann= 7 ,-1 , 0
  3210.9     .06       0  4809.7    .085       0  4974.2     .08       0
  5080.9    .085       0  6171.5     .06       0  7924.8     .99       0
  8451.5     .06       0
#Block Obstruct= 2 ,-1
    7920    8425   203.4    8500    8510     100
Bank Sta=4974.2,5049.9
Exp/Cntr=0.3,0.1

Type RM Length L Ch R = 1 ,18798.2 ,820.32,889.4,498.76
BEGIN DESCRIPTION:
Cross Section K166-00-00-X18
END DESCRIPTION:
XS GIS Cut Line= 4
 2953341.741854713919470.6012477      2952245.41     13919430.06
      2952147.23     13919292.15 2948183.713265613919064.9793698
#Sta/Elev= 30
  3819.5   209.9  4039.5   203.2  4279.5   201.7  4529.5   208.1  4629.5   206.5
  4829.5   197.8  4903.7  192.09  4940.3  191.78  4982.5  193.36  4986.6  191.19
  4988.9   187.8  4995.5  186.21  5011.2  187.66    5015  190.94  5022.8  192.45
  5042.8  193.62  5215.9   197.8  5415.9   199.4  5545.9   197.3  5765.9   198.9
    6377  197.43  6615.9   198.5  6715.9   200.9  8075.4  203.39  8275.9   204.8
  8325.9   200.4  8605.9   200.5  8665.9   203.5  8745.9   203.7  9055.9   210.8
#Mann= 6 ,-1 , 0
  3819.5     .06       0  4940.3    .085       0  4982.5     .08       0
  5042.8    .085       0    6377     .06       0  8075.4     .99       0
#XS Ineff= 2 , 0
          4529.5   208.1
Permanent Ineff=
       F       F
#Block Obstruct= 2 ,-1
    8275    8665   203.5    8800    8810     100
Bank Sta=4982.5,5042.8
Exp/Cntr=0.3,0.1

Type RM Length L Ch R = 1 ,17908.8 ,1087.58,1205.1,1036.7
BEGIN DESCRIPTION:
Cross Section K166-00-00-X17
END DESCRIPTION:
XS GIS Cut Line= 4
 2953072.7115274 13918710.552874      2951821.37     13918660.12
      2951723.04      13918721.3 2948342.234839113918871.6194052
#Sta/Elev= 30
  3697.8   209.4  3807.8   209.1  3857.8   205.6  3947.8   202.5  4197.8   197.8
  4527.8   198.5  4801.9  197.06  4932.1  196.53  4951.9  194.32    4973  192.76
  4978.9  189.94  4979.8  188.64  4980.1  186.69  4989.2  184.25    5008  183.79
  5019.7  186.56  5020.3  188.62  5030.9  194.69  5052.5   193.4    5146   197.8
    5306   199.1    5606   198.7  5767.4   196.6    5986   196.7    6416   200.7
  7551.4  202.12    7666   202.3    7806   199.9    7966   200.3 8450.14  210.03
#Mann= 6 ,-1 , 0
  3697.8    .055       0  4801.9    .085       0  4951.9     .08       0
  5030.9    .085       0  5767.4     .06       0  7551.4     .99       0
#Block Obstruct= 2 ,-1
    7665    8060   202.3    8500    8510     100
Bank Sta=4951.9,5030.9
Exp/Cntr=0.3,0.1

Type RM Length L Ch R = 1 ,16703.7 ,508.53,847.1,932.17
BEGIN DESCRIPTION:
Cross Section K166-00-00-X16
END DESCRIPTION:
XS GIS Cut Line= 4
  2952693.82889813917992.5738086      2951769.58     13917655.12
      2951669.16     13917589.73 2948301.837702213918293.5276903
#Sta/Elev= 30
  3950.1   212.7  4100.1   211.8  4250.1   205.3  4280.1   202.9  4310.1   203.1
  4390.1   200.9  4430.1   198.2  4510.1   195.8  4860.1   196.3  4978.8  193.38
  4987.1  190.21  4989.1  188.58  4989.4   186.8  4999.5  184.95  5010.4  187.02
  5010.9  188.59  5013.5   191.4  5044.3  192.13  5058.4  193.46  5213.9     197
  5243.9   196.2  6183.9   195.7  6203.9   196.4  6283.9   195.7  6443.9     199
  7423.9   201.1  7503.9   200.1  7653.9   200.2  7693.9   201.7  8493.9   213.6
#Mann= 4 ,-1 , 0
  3950.1    .055       0  4100.1    .055       0  4978.8     .08       0
  5058.4     .06       0
Bank Sta=4978.8,5058.4
Exp/Cntr=0.3,0.1

Type RM Length L Ch R = 1 ,15856.6 ,1225.13,1117.3,322.82
BEGIN DESCRIPTION:
Cross Section K166-00-00-X15
Prelimnary model: possible spillage to Waller County (Snake Creek) on ROB, flows excluded by RASlevee option (not a regulatory flood control levee).
END DESCRIPTION:
XS GIS Cut Line= 5
 2953225.312856213917865.9286493      2952156.51     13917295.01
      2952175.39     13917120.31      2952006.67     13916922.43
 2945244.066065913915896.2614064
#Sta/Elev= 30
  3681.3   208.9  3931.3   201.4  4161.3   203.5  4451.3   197.3  4841.3   196.4
  4877.3   191.6  4947.7  194.23  4989.5  188.41  4996.1  183.02  5006.8  185.74
  5012.8  192.97  5024.2  194.49  6323.4  195.61  6476.9  194.79  7738.8   198.6
  9178.8   195.8  9318.8   199.4  9368.8   196.5  9638.8   196.8  9728.8   192.4
  9768.8     196 10078.8   199.9 10456.3  200.54 10508.8   196.8 10538.8   199.7
 11308.8   201.7 11398.8   206.3 11858.8   205.5 11918.8   208.8 12168.8   209.4
#Mann= 6 ,-1 , 0
  3681.3    .055       0  4947.7     .08       0  5024.2    .085       0
  6323.4     .09       0  6476.9     .06       0 10456.3     .99       0
Bank Sta=4947.7,5024.2
Exp/Cntr=0.3,0.1

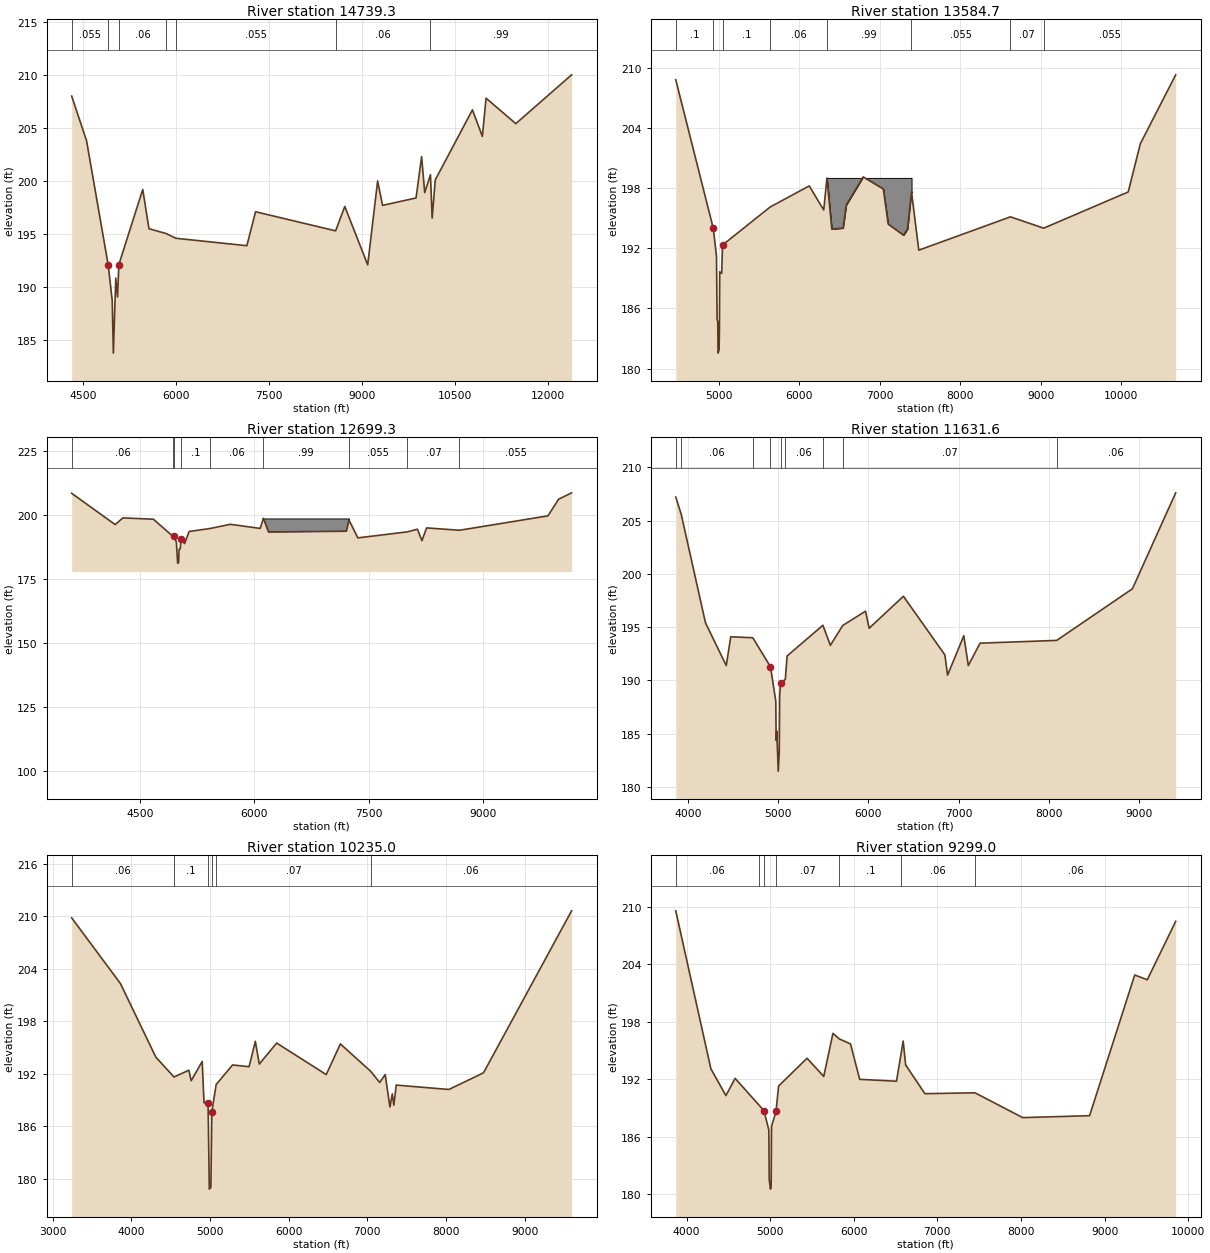
Type RM Length L Ch R = 1 ,14739.3 ,637.62,1154.6,774.13
BEGIN DESCRIPTION:
Cross Section K166-00-00-X14
Prelimnary model: possible spillage to Waller County (Snake Creek) on ROB, flows excluded by RASlevee option (not a regulatory flood control levee).
END DESCRIPTION:
XS GIS Cut Line= 4
  2952620.16872713916589.4831642      2952024.38     13916494.08
      2951941.56      13916586.1 2944682.589860413915498.2245763
#Sta/Elev= 30
    4321     208    4561   203.8  4910.9  192.08  4975.5  188.74  4993.9  183.78
  5033.1  190.84  5061.5  189.07  5082.6  192.12  5468.2   199.2  5568.2   195.5
  5843.3  195.05  6003.7   194.6  7148.2   193.9  7288.2   197.1  8580.6   195.3
  8728.2   197.6  9098.2   192.1  9258.2     200  9338.2   197.7  9878.2   198.4
  9968.2   202.3 10018.2   198.9   10111  200.59 10138.2   196.5 10188.2   200.1
 10788.2   206.7 10948.2   204.2 11008.2   207.8 11488.2   205.4 12388.2     210
#Mann= 7 ,-1 , 0
    4321    .055       0  4910.9     .08       0  5082.6     .06       0
  5843.3     .09       0  6003.7    .055       0  8580.6     .06       0
   10111     .99       0
Bank Sta=4910.9,5082.6
Exp/Cntr=0.3,0.1

Type RM Length L Ch R = 1 ,13584.7 ,1041.15,885.4,498.9
BEGIN DESCRIPTION:
Cross Section K166-00-00-X13
Prelimnary model: possible spillage to Waller County (Snake Creek) on ROB, flows excluded by RASlevee option (not a regulatory flood control levee).
END DESCRIPTION:
XS GIS Cut Line= 4
  2952860.42468813916255.6359017      2952472.41     13916010.97
      2952414.25     13915908.22 2946879.033959913914883.9405806
#Sta/Elev= 30
  4469.2  208.78  4935.3  193.96  4974.8  191.19  4982.3  184.86  4990.4   184.7
  4994.1  181.54  5007.3  181.89  5011.1  183.88    5015  189.64  5039.3  189.49
  5049.6  192.31  5640.9   196.1    6126   198.2    6306   195.8    6346     199
    6406   193.9    6546     194    6586   196.3    6796   199.1    7046   197.9
    7106   194.4    7296   193.3    7346   193.9  7395.5  197.63    7486   191.8
  8623.9  195.12  9036.7  193.99   10086   197.6   10236   202.410675.21  209.27
#Mann= 8 ,-1 , 0
  4469.2      .1       0  4935.3     .08       0  5049.6      .1       0
  5640.9     .06       0    6346     .99       0  7395.5    .055       0
  8623.9     .07       0  9036.7    .055       0
#Block Obstruct= 2 ,-1
    6346    6796     199 6796.01    7396     199
Bank Sta=4935.3,5049.6
Exp/Cntr=0.3,0.1

Type RM Length L Ch R = 1 ,12699.3 ,752.49,1067.7,808.45
BEGIN DESCRIPTION:
Cross Section K166-00-00-X12
Prelimnary model: possible spillage to Waller County (Snake Creek) on ROB, flows excluded by RASlevee option (not a regulatory flood control levee).
END DESCRIPTION:
XS GIS Cut Line= 4
 2953570.702510613915277.7094068      2952264.34     13915217.64
      2952183.71     13915357.56 2947170.148674613914538.3697288
#Sta/Elev= 30
 3606.84  208.51  4177.4   196.3  4277.4   198.9  4677.4   198.4  4936.9  191.62
  4951.1  191.83  4978.6  189.38  4995.3  181.21  5008.4  181.43  5013.4  186.58
  5028.1  186.72    5040  190.57    5086  188.87  5146.1   193.6  5417.2  194.75
  5686.1   196.4  6076.1   194.8  6119.4  198.74  6186.1   193.4  7206.1   193.7
  7239.7  198.06  7356.1   191.1  8006.4  193.46  8136.1   194.5  8196.1     190
  8256.1     195  8687.6  194.08  9846.1   199.7  9986.1   206.2 10156.1   208.7
#Mann= 9 ,-1 , 0
 3606.84     .06       0  4936.9      .1       0  4951.1     .08       0
    5040      .1       0  5417.2     .06       0  6119.4     .99       0
  7239.7    .055       0  8006.4     .07       0  8687.6    .055       0
#Block Obstruct= 2 ,-1
    6110    7245   198.510000.01   12000     100
Bank Sta=4951.1,5040
Exp/Cntr=0.3,0.1

Type RM Length L Ch R = 1 ,11631.6 ,858.04,1396.6,1884.51
BEGIN DESCRIPTION:
Cross Section K166-00-00-X11
Prelimnary model: possible spillage to Waller County (Snake Creek) on ROB, flows excluded by RASlevee option (not a regulatory flood control levee).
END DESCRIPTION:
XS GIS Cut Line= 4
 2952840.713994613914728.4393845      2951833.62     13914395.52
      2951678.88     13914475.39 2947382.077262313914138.7851234
#Sta/Elev= 30
  3862.4   207.2  3922.4   205.6  4192.4   195.4  4422.4   191.4  4472.4   194.1
  4716.5  194.01  4912.9  191.29  4971.8  188.07  4975.6  184.39  4982.8  185.23
    4999   181.5  5010.5  183.27  5014.4  188.55  5024.3  189.73  5077.5  190.11
  5097.2   192.3  5494.4  195.18  5577.2   193.3  5714.2  195.16  5967.2   196.5
  6007.2   194.9  6387.2   197.9  6847.2   192.4  6877.2   190.5  7057.2   194.2
  7107.2   191.4  7237.2   193.5  8087.4  193.76  8927.2   198.6  9407.2   207.6
#Mann= 9 ,-1 , 0
  3862.4     .06       0  3922.4     .06       0  4716.5      .1       0
  4912.9     .08       0  5024.3      .1       0  5077.5     .06       0
  5494.4      .1       0  5714.2     .07       0  8087.4     .06       0
Bank Sta=4912.9,5024.3
Exp/Cntr=0.3,0.1

Type RM Length L Ch R = 1 ,10235.0 ,821.45,936,704.12
BEGIN DESCRIPTION:
Cross Section K166-00-00-X10
Prelimnary model: possible spillage to Waller County (Snake Creek) on ROB, flows excluded by RASlevee option (not a regulatory flood control levee).
END DESCRIPTION:
XS GIS Cut Line= 5
 2953316.878755513914403.2325943      2951857.34     13913546.43
      2951837.04     13913414.48      2951469.23     13912938.97
  2947540.01557213913019.1528652
#Sta/Elev= 30
  3239.4   209.8  3859.4   202.3  4309.4   193.9  4541.1  191.62  4729.4   192.4
  4759.4   191.2  4899.4   193.4  4922.6  188.67  4973.8  188.69  4989.8  178.82
  5009.6  179.02    5022  187.66  5076.8  190.76  5285.3     193  5495.3   192.8
  5575.3   195.7  5625.3   193.1  5846.5   195.5  6476.5   191.9  6656.5   195.4
  7040.4  192.29  7156.5     191  7226.5   191.9  7286.5   188.2  7316.5   189.7
  7336.5   188.4  7366.5   190.7  8036.5   190.2  8476.5   192.1  9596.5   210.6
#Mann= 6 ,-1 , 0
  3239.4     .06       0  4541.1      .1       0  4973.8     .08       0
    5022      .1       0  5076.8     .07       0  7040.4     .06       0
Bank Sta=4973.8,5022
Exp/Cntr=0.3,0.1

Type RM Length L Ch R = 1 ,9299.0  ,1037.93,1077.3,670.13
BEGIN DESCRIPTION:
Cross Section K166-00-00-X9
Prelimnary model: possible spillage to Waller County (Snake Creek) on ROB, flows excluded by RASlevee option (not a regulatory flood control levee).
END DESCRIPTION:
XS GIS Cut Line= 4
 2953243.125563813913605.2672771      2952465.76     13912877.48
      2952382.53     13912758.58 2947789.196026913911472.6113613
#Sta/Elev= 30
  3870.5   209.6  4290.5   193.1  4470.5   190.3  4580.5   192.1  4863.9  189.33
  4925.3  188.73  4983.8  186.71  4988.7   181.5  5003.5  180.53  5011.4  180.84
  5016.1   187.1  5070.2  188.66  5100.5   191.3  5440.5   194.2  5640.5   192.3
  5750.5   196.8  5828.7  196.21  5960.5   195.7  6070.5     192  6510.5   191.8
  6567.2  194.74  6590.5     196  6620.5   193.5  6850.5   190.5    7450  190.59
  8020.5     188  8820.5   188.2  9360.5   202.9  9510.5   202.4  9850.5   208.5
#Mann= 7 ,-1 , 0
  3870.5     .06       0  4863.9      .1       0  4925.3     .08       0
  5070.2     .07       0  5828.7      .1       0  6567.2     .06       0
    7450     .06       0
Bank Sta=4925.3,5070.2
Exp/Cntr=0.3,0.1

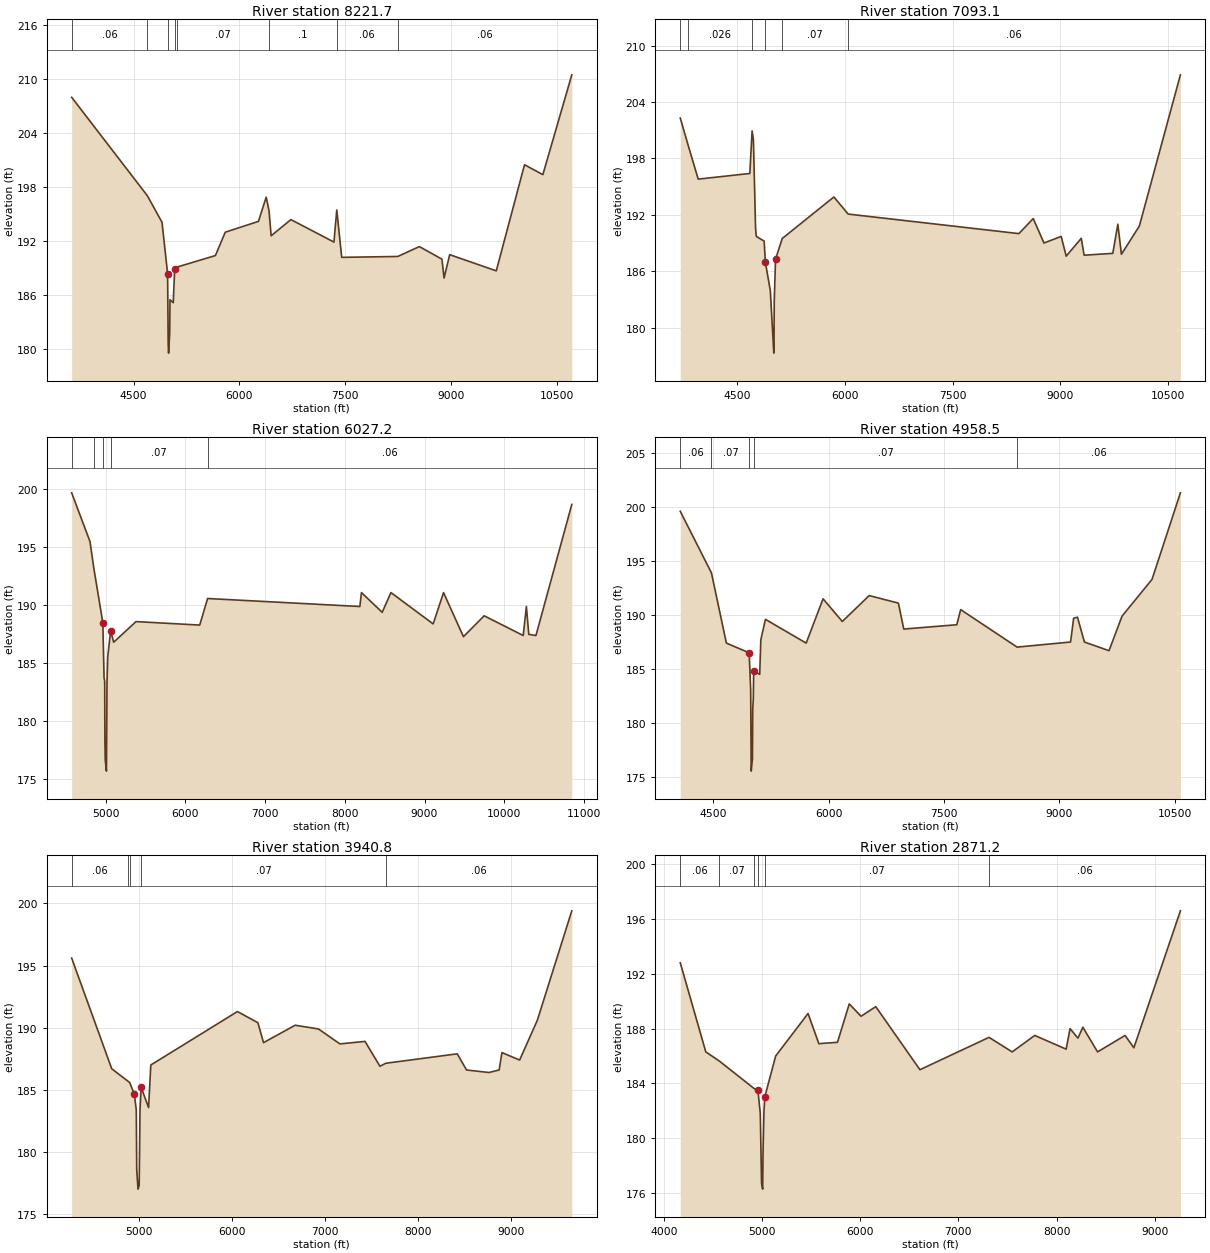
Type RM Length L Ch R = 1 ,8221.7  ,945.89,1128.6,1150.1
BEGIN DESCRIPTION:
Cross Section K166-00-00-X8
Prelimnary model: possible spillage to Waller County (Snake Creek) on ROB, flows excluded by RASlevee option (not a regulatory flood control levee).
END DESCRIPTION:
XS GIS Cut Line= 4
 2954227.213720813913386.7599524      2953331.27     13912407.14
      2953196.47     13912440.35 2947685.010072913911340.8357628
#Sta/Elev= 30
  3622.2     208  4695.1  197.05  4902.2   194.1  4981.4   188.4  4989.8  180.55
  4995.5  179.55  5011.4  181.82    5015  185.49  5061.4  185.16  5081.5  188.88
    5115  189.12  5658.6   190.4  5798.6     193  6268.6   194.2  6378.6   196.9
  6418.6  195.37  6448.6   192.6  6728.6   194.4  7338.6   191.9  7378.3  195.47
  7448.6   190.2  8243.4   190.3  8548.6   191.4  8868.6     190  8898.6   187.9
  8978.6   190.5  9638.6   188.7 10038.6   200.5 10298.6   199.4 10708.6   210.5
#Mann= 8 ,-1 , 0
  3622.2     .06       0  4695.1      .1       0  4981.4     .08       0
  5081.5      .1       0    5115     .07       0  6418.6      .1       0
  7378.3     .06       0  8243.4     .06       0
Bank Sta=4981.4,5081.5
Exp/Cntr=0.3,0.1

Type RM Length L Ch R = 1 ,7093.1  ,1376.1,1065.9,679.81
BEGIN DESCRIPTION:
Cross Section K166-00-00-X7
Prelimnary model: possible spillage to Waller County (Snake Creek) on ROB, flows excluded by RASlevee option (not a regulatory flood control levee).
Right bank changed from 5124.9 to 5031.3 by JJA on 3/12/03.
END DESCRIPTION:
XS GIS Cut Line= 4
 2954740.710904613912036.6897432      2953631.77     13911583.61
      2953549.25     13911396.72 2948018.762766813910712.4065291
#Sta/Elev= 30
  3702.8   202.3  3815.1  199.34  3952.8   195.8  4672.8   196.4  4704.5  200.93
  4722.8     200  4752.8   190.6  4762.8   189.7  4872.8   189.2    4889  186.98
  4958.4  183.94  5007.3  177.28    5010  177.78  5013.4  182.83  5031.3  187.28
  5124.9  189.48    5845   193.9  6044.1  192.08    8425     190    8625   191.6
    8775     189    9015   189.7    9085   187.6    9295   189.5    9335   187.7
    9735   187.9    9805     191    9855   187.8   10105   190.8 10677.7   206.9
#Mann= 6 ,-1 , 0
  3702.8     .06       0  3815.1    .026       0  4704.5      .1       0
    4889     .08       0  5124.9     .07       0  6044.1     .06       0
#Block Obstruct= 2 , 0
         4704.85  201.09
Bank Sta=4889,5031.3
Exp/Cntr=0.3,0.1

Type RM Length L Ch R = 1 ,6027.2  ,983.33,1068.7,817.39
BEGIN DESCRIPTION:
Cross Section K166-00-00-X6
Prelimnary model: possible spillage to Waller County (Snake Creek) on ROB, flows excluded by RASlevee option (not a regulatory flood control levee).
END DESCRIPTION:
XS GIS Cut Line= 4
 2954524.689930513910514.5868008      2954230.54     13910691.11
      2954068.65     13910718.09  2948299.18308913910638.1654021
#Sta/Elev= 30
  4571.4   199.7  4801.4   195.5  4848.7  193.23  4962.5  188.51    4978  183.75
    4986  183.46  4987.5  179.88  4989.1  178.17  4992.7  176.66  5007.8  175.71
  5014.9  183.29    5024  185.55  5060.3   187.8  5098.5  186.82  5378.6   188.6
  6178.6   188.3  6277.4  190.59  8188.6   189.9  8208.6   191.1  8468.6   189.4
  8578.6   191.1  9108.6   188.4  9238.6   191.1  9488.6   187.3  9748.6   189.1
 10238.6   187.4 10278.6   189.9 10308.6   187.5 10398.6   187.4 10848.6   198.7
#Mann= 5 ,-1 , 0
  4571.4     .06       0  4848.7     .07       0  4962.5     .08       0
  5060.3     .07       0  6277.4     .06       0
Bank Sta=4962.5,5060.3
Exp/Cntr=0.3,0.1

Type RM Length L Ch R = 1 ,4958.5  ,1150.3,1017.7,752.03
BEGIN DESCRIPTION:
Cross Section K166-00-00-X5
Prelimnary model: possible spillage to Waller County (Snake Creek) on ROB, flows excluded by RASlevee option (not a regulatory flood control levee).
Right bank station moved from 5035 to 5024.4 by JJA on 3/12/03.
END DESCRIPTION:
XS GIS Cut Line= 4
 2954421.500242413909718.2519607      2953569.78     13909905.54
      2953487.56     13910013.68 2947989.262437213909928.0171854
#Sta/Elev= 30
  4069.5   199.6    4475   193.9  4669.5   187.4  4966.1   186.5  4985.4  183.06
  4992.4  175.55  5008.1   176.7  5012.4  181.33  5019.7  182.22  5024.4  184.81
    5103  184.51  5117.4   187.7  5177.4   189.6  5707.4   187.4  5927.4   191.5
  6177.4   189.4  6527.4   191.8  6907.4   191.1  6977.4   188.7  7667.4   189.1
  7717.4   190.5  8451.4  187.03  9147.4   187.5  9187.4   189.7  9237.4   189.8
  9327.4   187.5  9647.4   186.7  9817.4   189.9 10207.4   193.310576.41  201.31
#Mann= 5 ,-1 , 0
  4069.5     .06       0    4475     .07       0  4966.1     .08       0
  5024.4     .07       0  8451.4     .06       0
Bank Sta=4966.1,5024.4
Exp/Cntr=0.3,0.1

Type RM Length L Ch R = 1 ,3940.8  ,618,1069.6,896
BEGIN DESCRIPTION:
Cross Section K166-00-00-X4
Changed left bank station from 4904.1 to4954.6 by JJA on 3/12/03.
END DESCRIPTION:
XS GIS Cut Line= 4
      2953320.95      13909013.2      2952730.17     13909320.44
      2952681.13     13909444.85      2948123.28      13909777.5
#Sta/Elev= 30
  4281.8   195.6  4711.8   186.7  4891.4  185.67  4904.1   185.6  4954.6  184.66
  4975.5  183.39  4980.1  178.61  4993.9  177.02  5006.7  177.32  5015.6  183.41
    5028   185.2  5107.6  183.58  5131.4     187  6061.4   191.3  6281.4   190.4
  6341.4   188.8  6681.4   190.2  6931.4   189.9  7161.4   188.7  7431.4   188.9
  7591.4   186.9  7653.4  187.14  8421.4   187.9  8521.4   186.6  8761.4   186.4
  8871.4   186.6  8901.4     188  9091.4   187.4  9281.4   190.6  9651.4   199.4
#Mann= 5 ,-1 , 0
  4281.8     .06       0  4891.4     .07       0  4904.1     .08       0
    5028     .07       0  7653.4     .06       0
Bank Sta=4954.6,5028
Exp/Cntr=0.3,0.1

Type RM Length L Ch R = 1 ,2871.2  ,964.28,1092.5,916
BEGIN DESCRIPTION:
Cross Section K166-00-00-X3
Left overbank reach length updated by JJA on 3/12/03.
END DESCRIPTION:
XS GIS Cut Line= 4
      2953207.22      13908743.7      2952442.28     13908671.93
       2952320.9     13908648.81      2948214.17      13909548.4
#Sta/Elev= 30
  4166.1   192.8  4426.1   186.3  4564.6  185.63  4916.4  183.64  4956.8  183.51
  4981.3  181.82  4994.4   176.7  5005.8  176.29  5009.3  178.89  5018.9  181.98
  5028.1  183.04    5138     186    5468   189.1    5578   186.9    5768     187
    5888   189.8    6008   188.9    6158   189.6    6608     185  7312.1  187.36
    7548   186.3    7778   187.5    8098   186.5    8138     188    8218   187.3
    8268   188.1    8418   186.3    8698   187.5    8788   186.6 9262.11  196.59
#Mann= 6 ,-1 , 0
  4166.1     .06       0  4564.6     .07       0  4916.4     .07       0
  4956.8     .08       0  5028.1     .07       0  7312.1     .06       0
Bank Sta=4956.8,5028.1
Exp/Cntr=0.3,0.1

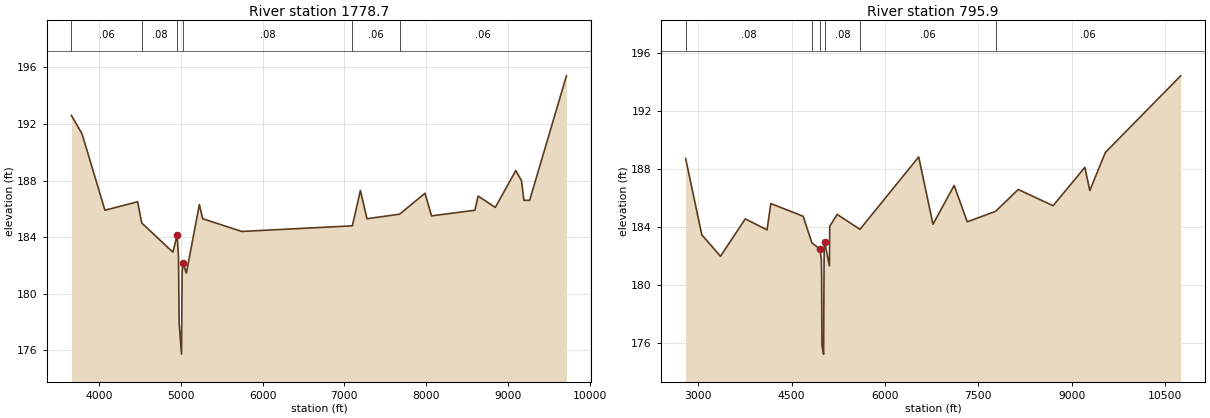
Type RM Length L Ch R = 1 ,1778.7  ,916.7,982.8,911
BEGIN DESCRIPTION:
Cross Section K166-00-00-X2
Overbank reach lengths updated by JJA on 3/12/03.
END DESCRIPTION:
XS GIS Cut Line= 4
      2953882.44     13908072.33      2952676.52     13907662.39
      2952555.03      13907661.5      2948225.75      13909385.8
#Sta/Elev= 30
  3662.4   192.6  3792.4   191.3  4072.4   185.9  4472.4   186.5  4522.5     185
  4903.3  182.94  4956.6  184.14  4972.1   182.6  4980.1  177.92  5009.1  175.73
  5016.7  181.56  5029.1  182.15  5068.1  181.45  5227.6   186.3  5267.6   185.3
  5747.6   184.4  7099.1   184.8  7197.6   187.3  7277.6   185.3  7676.4  185.62
  7987.6   187.1  8067.6   185.5  8597.6   185.9  8637.6   186.9  8847.6   186.1
  9097.6   188.7  9167.6     188  9197.6   186.6  9267.6   186.6  9717.6   195.4
#Mann= 6 ,-1 , 0
  3662.4     .06       0  4522.5     .08       0  4956.6     .08       0
  5029.1     .08       0  7099.1     .06       0  7676.4     .06       0
Bank Sta=4956.6,5029.1
Exp/Cntr=0.3,0.1

Type RM Length L Ch R = 1 ,795.9   ,0,0,0
BEGIN DESCRIPTION:
Cross Section K166-00-00-X1
END DESCRIPTION:
XS GIS Cut Line= 6
      2954616.37     13907917.77      2954003.17     13907181.23
      2952870.66     13906782.55      2952767.89     13906824.82
      2952726.39     13906841.89      2947281.32      13908311.6
#Sta/Elev= 30
  2796.5  188.74  3056.5  183.47  3356.5  181.99  3754.9  184.57  4104.9  183.81
  4164.9  185.63  4684.9  184.75  4825.8  182.91    4955  182.49  4977.3  181.79
  4981.8  180.47  4987.3  175.83  5013.3  175.23  5022.3   182.5  5030.2  182.97
  5107.6  181.32  5111.5  184.06  5231.5  184.88  5598.2  183.85  6541.5  188.85
  6771.5   184.2  7111.5  186.88  7321.5  184.37    7777  185.09  8141.5   186.6
  8701.5  185.48  9211.5  188.13  9291.5  186.53  9541.5  189.16 10751.5  194.45
#Mann= 6 ,-1 , 0
  2796.5     .08       0  4825.8     .08       0    4955     .08       0
  5030.2     .08       0  5598.2     .06       0    7777     .06       0
Bank Sta=4955,5030.2
Exp/Cntr=0.3,0.1

Chan Stop Cuts=-1
Use User Specified Reach Order=0
User Specified Reach Order=K166-00-00      ,K166-00-00_0008